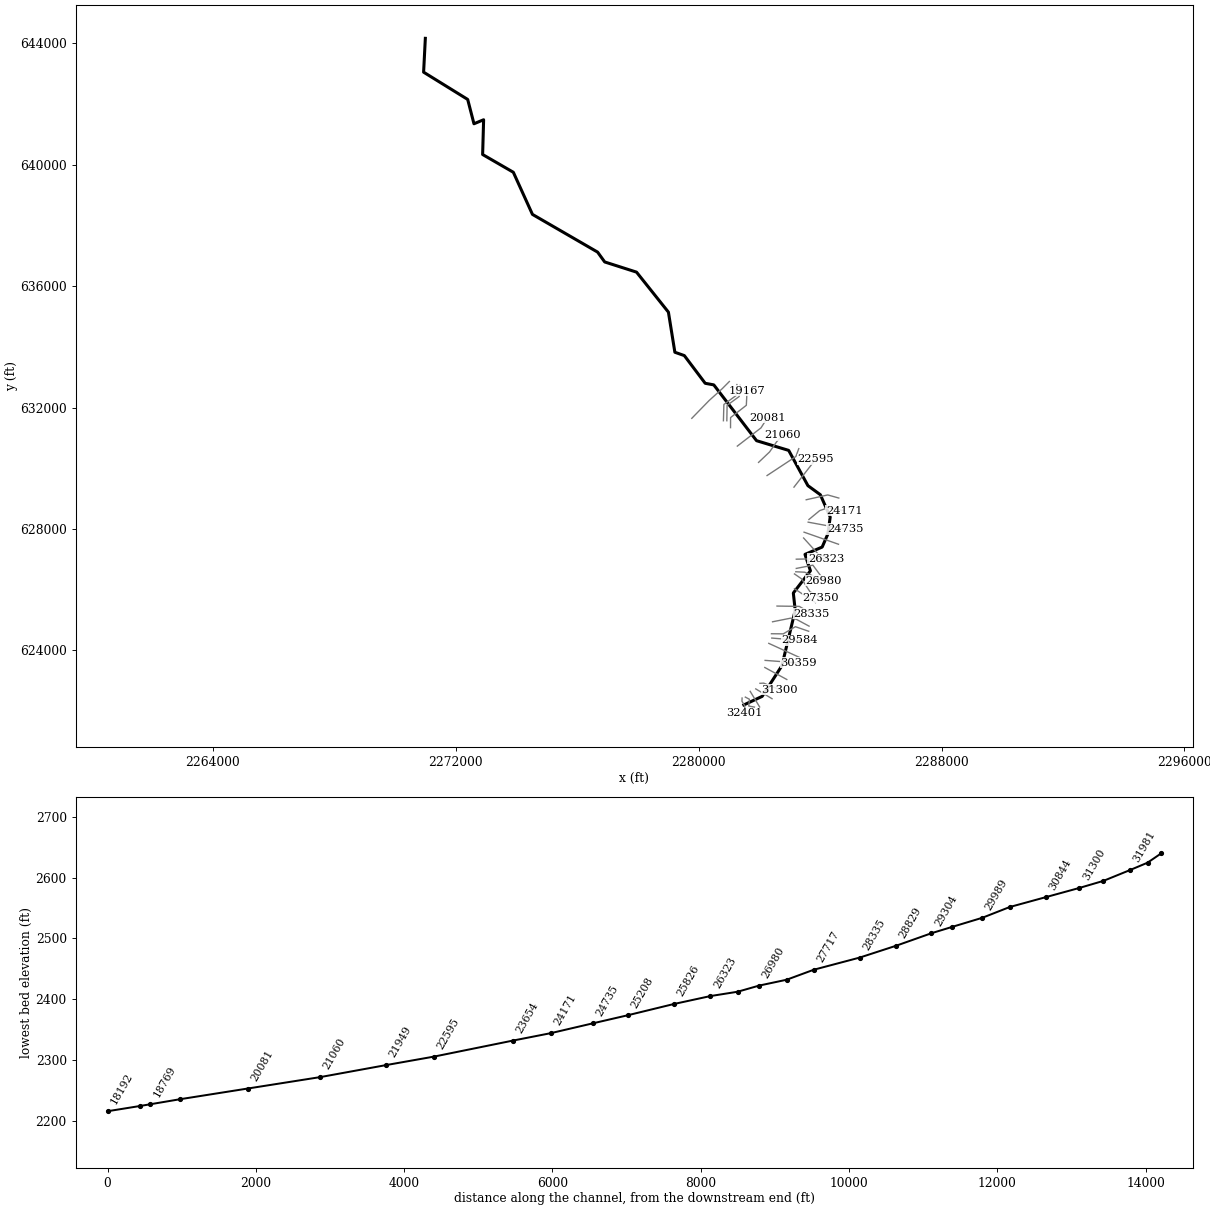
--- SHAVRRN.prj (project) ---

Proj Title=SHAVRRN
Current Plan=p01
Default Exp/Contr=0,0
English Units
Geom File=g01
Flow File=f01
Plan File=p01
Background Map Layer=Inundation Boundary (P100yr Value_0)
BEGIN DESCRIPTION:
----------MODEL BY WOOD PLC 2022----------
AFH study
Randolph County, WV
HEC-RAS Version: RAS 6.2
Vertical Datum: NAVD88
Projection: NAD 1983 StatePlane West Virginia S FIPS 4702 (US Feet)
Terrain: 1-meter LIDAR (FEMA Region III 3DEP collected 2016-2018)
Land Use: 2019 NLCD
Hydrologic Method:
WV SIR2010-5033 regression equations
Additional Model Notes:
None
END DESCRIPTION:
DSS Export Rating Curves= 0
DSS Export Rating Curve Sorted= 0
DSS Export Volume Flow Curves= 0
DXF OffsetX= 0
DXF OffsetY= 0
DXF ScaleX= 0
DXF ScaleY= 0

--- SHAVRRN.p01 (plan) ---

Plan Title=Floodplain
Program Version=6.20
Short Identifier=Floodplain
Geom File=g01
Flow File=f01
Subcritical Flow
K Sum by GR= 0
Std Step Tol= 0.01
Critical Tol= 0.01
Num of Std Step Trials= 20
Max Error Tol= 0.3
Flow Tol Ratio= 0.001
Split Flow NTrial= 30
Split Flow Tol= 0.02
Split Flow Ratio= 0.02
Log Output Level= 0
Friction Slope Method= 1
Unsteady Friction Slope Method= 2
Unsteady Bridges Friction Slope Method= 1
Parabolic Critical Depth
Global Vel Dist= 0 , 0 , 0
Global Log Level= 0
CheckData=True
Encroach Param=-1 ,0,0, 0
Mapping Interval=1HOUR
Computation Time Step Use Courant=        0
Computation Time Step Use Time Series=    0
Computation Time Step Count To Double=0
Computation Time Step Max Doubling=0
Computation Time Step Max Halving=0
Computation Time Step Residence Courant=0
Run HTab= 0
Run UNet= 0
Run Sediment= 0
Run PostProcess= 0
Run WQNet= 0
Run RASMapper=-1
UNET Theta= 0
UNET Theta Warmup= 0
UNET ZTol= 0
UNET ZSATol= 0
UNET MxIter= 0
UNET Max Iter WO Improvement= 0
UNET MaxInSteps= 0
UNET DtIC= 0
UNET DtMin= 0
UNET MaxCRTS= 0
UNET WFStab= 0
UNET SFStab= 0
UNET WFX= 1
UNET SFX= 1
UNET Gravity=32.174
UNET 1D Methodology=Finite Difference
UNET DSS MLevel= 1
UNET Pardiso=0
UNET DZMax Abort= 0
UNET Use Existing IB Tables= 0
UNET Froude Reduction=False
UNET Froude Limit= 0
UNET Froude Power= 0
UNET D1 Cores= 0
UNET WindReference=Eulerian
UNET WindDragFormulation=Hsu (1988)
UNET D2 Coriolis=0
UNET D2 Cores= 0
UNET D2 Theta= 1
UNET D2 Theta Warmup= 1
UNET D2 Z Tol= 0.01
UNET D2 Volume Tol= 0.01
UNET D2 Max Iterations= 20
UNET D2 Equation= 0
UNET D2 RampUpFraction=0.1
UNET D2 TimeSlices= 1
UNET D2 Turbulence Formulation=Non-Conservative (original)
UNET D2 Eddy Viscosity=0.3
UNET D2 Transverse Eddy Viscosity=0.1
UNET D2 Smagorinsky Mixing=0
UNET D2 BCVolumeCheck=0
UNET D2 Cores=0
UNET D2 SolverType=PARDISO (Direct)
UNET D2 Minimum Iterations= 2147483647
UNET D2 Maximum Iterations= 2147483647
UNET D2 Restart Number= 10
UNET D2 Relaxation Coeff=1.3
UNET D2 SOR Precondition Iterations= 10
UNET D2 ILUT Maximum Fill= 8
UNET D2 ILUT Tolerance=1E-08
UNET D1D2 MaxIter= 0
UNET D1D2 ZTol=0.01
UNET D1D2 QTol=0.1
UNET D1D2 MinQTol=1
Write IC File= 0
Write IC File at Fixed DateTime=0
Write IC File at Sim End=0
Echo Input=False
Echo Parameters=False
Echo Output=False
Write Detailed= 0
HDF Write Warmup=0
HDF Write Time Slices=0
HDF Flush=0
HDF Compression= 1
HDF Chunk Size= 1
HDF Spatial Parts= 1
HDF Use Max Rows=0
HDF Fixed Rows= 1
Calibration Method= 0
Calibration Iterations= 20
Calibration Max Change=0.05
Calibration Tolerance=0.2
Calibration Maximum=1.5
Calibration Minimum=0.5
Calibration Optimization Method= 1
WQ AD Non Conservative
WQ ULTIMATE=-1
WQ Max Comp Step=1HOUR
WQ Output Interval=15MIN
WQ Output Selected Increments= 0
WQ Output face flow=0
WQ Output face velocity=0
WQ Output face area=0
WQ Output face dispersion=0
WQ Output cell volume=0
WQ Output cell surface area=0
WQ Output cell continuity=0
WQ Output cumulative cell continuity=0
WQ Output face conc=0
WQ Output face dconc_dx=0
WQ Output face courant=0
WQ Output face peclet=0
WQ Output face adv mass=0
WQ Output face disp mass=0
WQ Output cell mass=0
WQ Output cell source sink temp=0
WQ Output nsm pathways=0
WQ Output nsm derived pathways=0
WQ Create Restart=0
WQ Fixed Restart=0
WQ System Summary=0
WQ Write To DSS=0
Sorting and Armoring Iterations= 10
XS Update Threshold= 0.02
Bed Roughness Predictor= 0
Hydraulics Update Threshold= 0.02
Energy Slope Method= 1
Volume Change Method= 1
Sediment Retention Method= 0
Sediment TS Multiplier= 1
Warm Up Method= 0
XS Weighting Method= 0
Number of US Weighted Cross Sections= 1
Number of DS Weighted Cross Sections= 1
Upstream XS Weight=0
Main XS Weight=1
Downstream XS Weight=0
Number of DS XS's Weighted with US Boundary= 1
Upstream Boundary Weight= 1
Weight of XSs Associated with US Boundary= 0
Number of US XS's Weighted with DS Boundary= 1
Downstream Boundary Weight= 0.5
Weight of XSs Associated with DS Boundary= 0.5
Percentile Method= 0
Sediment Output Level= 3
Mass or Volume Output= 0
Output Increment Type= 1
Profile and TS Output Increment= 1
Transport Output Increment 1
XS Output Flag= 0
XS Output Increment= 10
Read HDF5 Sediment Hotstart= 0
Sediment Hotstart Type= 0
Write Gradation File= 0
Read Gradation Hotstart= 0
Write HDF5 File= 1
Write Binary Output= 1
Write DSS Sediment File= 0
DSS Sediment Output Type= 1
SV Curve= 0
Specific Gage Flag= 0
Subcell Erosion Methods= 0
Subcell Deposition Methods= 0
Advection Scheme= 1
Matrix Solver= 0
Implicit Weighting Factor= 1
Maximum Outer Loop Convergence Iterations= 5
Convergence Maximum Absolute= 0.001
Convergence RMSE= 0.0001
Grain Fractions Max Abs Error= 0.001
Max Subgrid Regions= 1
Max Subgrid Length Scale= 3.402823E+38
Initial Layer Thickness= 3.402823E+38
Min Layer Thickness= 3.402823E+38
Max Layer Thickness= 3.402823E+38
Number of Layers= 5

--- SHAVRRN.f01 (steady flow) ---

Flow Title=Flow
Program Version=4.00
Number of Profiles=1
Profile Names=P100yr
River Rch & RM=SHAVRRN,Main,32401
     666
River Rch & RM=SHAVRRN,Main,26690
     812
River Rch & RM=SHAVRRN,Main,22595
    1290
River Rch & RM=SHAVRRN,Main,19167
    1450
River Rch & RM=SHAVRRN,Main,14298
    1620
Boundary for River Rch & Prof#=SHAVRRN,Main      ,1
Up Type=0
Dn Type=3
Dn Slope=0.009512

--- SHAVRRN.g01 (geometry) ---

Geom Title=Geometry
Program Version=6.20

River Reach=SHAVRRN         ,Main
Reach XY= 30
     2281488.293      622206.485     2282092.338      622489.193
     2282742.655      623499.069     2283180.478      625322.545
     2283118.701      625893.414     2283682.104      626624.841
     2283502.473      627165.553     2284068.428      627406.942
     2284255.278      627834.944     2284333.044      628395.751
     2284008.202      629131.352     2283599.027      629429.782
     2282965.342       630591.33     2281907.065      630910.983
      2280498.39      632749.349      2280215.53      632801.523
     2279528.032      633714.275     2279216.372      633824.265
     2279004.017      635145.319     2277953.427      636463.375
     2276904.992      636798.595     2276671.006      637122.962
     2274524.845      638365.382     2273895.245      639752.956
     2272883.983      640337.927     2272916.492      641482.683
     2272598.469      641350.791     2272391.492      642152.127
     2270939.555      643050.279      2270996.61      644164.802

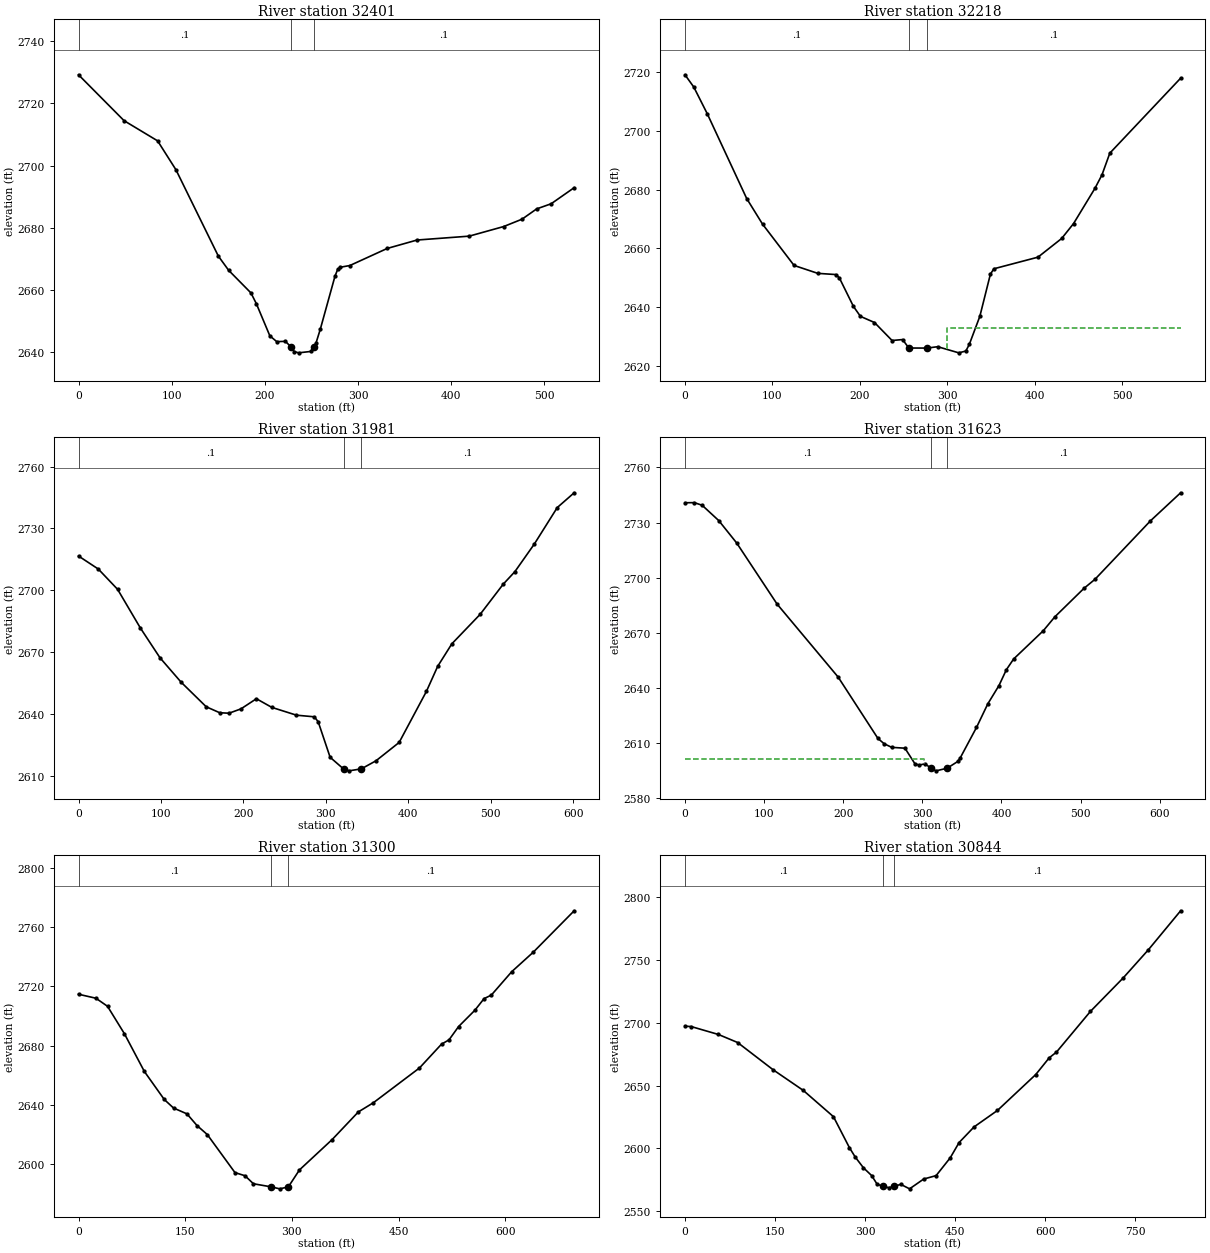
Type RM Length L Ch R = 1 ,32401   ,189.3,183.5,175.2
XS GIS Cut Line= 4
 2281430.4506208622434.0469483842281425.94656358622329.552820961
2281519.91321349622175.3878515772281515.97594684621928.457328658
#Sta/Elev= 30
       0 2729.23    48.9 2714.45    84.9 2707.95   104.6 2698.64   150.1 2670.84
   161.2 2666.25   185.1 2658.98   190.9 2655.52   205.4 2645.16   212.8 2643.29
   222.1 2643.38   228.12641.602   231.5  2640.1   236.2 2639.68   249.1 2640.12
   252.92641.666     255 2642.87   259.6 2647.32   275.3 2664.33   278.2 2666.56
   281.1 2667.25   291.3  2667.8   331.4  2673.3   363.4 2676.01   419.4 2677.26
   456.4 2680.35   476.1 2682.72   491.8 2686.03   507.4 2687.69   532.1 2692.87
#Mann= 3 ,-1,0
       0      .1       0   228.1    .045       0   252.9      .1       0
Bank Sta=228.1,252.9
XS Rating Curve= 0 ,0
Exp/Cntr(USF)=0,0
Exp/Cntr=0.3,0.1

Type RM Length L Ch R = 1 ,32218   ,232,237.2,245.1
XS GIS Cut Line= 4
2281537.62544853622464.2299480852281672.20667815622393.696412075
2281650.31696008 622169.124119262281836.78492884622135.884177002
#Sta/Elev= 30
       0 2719.07    10.1 2714.88    25.5  2705.8    70.6 2676.94    88.7 2668.24
   124.8 2654.16   151.9 2651.47   172.6 2651.06   176.6 2649.93   192.7 2640.22
   200.7 2636.83   216.8 2634.73   236.9 2628.61   248.9 2628.93   256.12626.054
     277 2626.03   289.1  2626.5   313.2 2624.41   321.3 2625.02   325.3 2627.32
   337.3 2636.83   349.4 2651.21   353.4 2653.03   403.8 2656.98   430.9 2663.34
   444.5 2668.41   468.9 2680.37     477 2684.98     486 2692.39     567 2717.91
#Mann= 3 ,-1,0
       0      .1       0   256.1    .045       0     277      .1       0
#XS Ineff= 2 , 0
                          299.67         2632.73
Permanent Ineff=
       F       F
Bank Sta=256.1,277
XS Rating Curve= 0 ,0
Exp/Cntr(USF)=0,0
Exp/Cntr=0.3,0.1

Type RM Length L Ch R = 1 ,31981   ,354.8,357.4,364.3
XS GIS Cut Line= 2
2281697.63117764622653.6980450362282009.02278767622139.654752288
#Sta/Elev= 30
       0 2716.61      24 2710.28    47.4 2700.42      75 2681.65    98.8 2667.18
   124.5 2655.29   154.9 2643.37   171.2 2640.49   182.5 2640.26     197 2642.37
   215.7 2647.29   234.4 2643.09   264.3  2639.3   285.9 2638.51   290.6 2636.13
   305.1 2618.85   321.4 2613.18     328 2612.27     343 2613.24   360.7 2617.15
   388.8 2626.07   421.8 2650.82   435.5 2663.02   452.7 2673.97     487 2688.28
     515 2702.94   529.1    2709   552.7 2722.43   580.5 2740.14     601 2747.32
#Mann= 3 ,-1,0
       0      .1       0   321.4    .045       0     343      .1       0
Bank Sta=321.4,343
XS Rating Curve= 0 ,0
Exp/Cntr(USF)=0,0
Exp/Cntr=0.3,0.1

Type RM Length L Ch R = 1 ,31623   ,322.4,323.4,325.6
XS GIS Cut Line= 2
2281880.51196449 622735.25299052 2282416.7975151622411.504570568
#Sta/Elev= 30
       0 2740.77    11.8 2740.83    21.7  2739.4    42.7 2731.04    65.4  2718.8
   116.4 2685.51   193.6 2645.68   243.9  2612.2   251.8 2609.31   261.3 2607.37
     278 2606.91   290.4 2598.56   295.5 2597.69   303.3 2598.37   311.2 2595.96
   317.3 2594.56   331.3 2595.98   345.1 2599.77     348 2601.73   368.4 2618.21
   382.7 2631.09   396.8 2641.06   406.2 2649.74   415.4 2655.58   452.9    2671
   467.4 2678.54   504.2 2694.07   518.2 2699.04   588.3 2730.92   626.4 2746.21
#Mann= 3 ,-1,0
       0      .1       0   311.2    .045       0   331.3      .1       0
#XS Ineff= 2 , 0
           302.3 2600.87
Permanent Ineff=
       F       F
Bank Sta=311.2,331.3
XS Rating Curve= 0 ,0
Exp/Cntr(USF)=0,0
Exp/Cntr=0.3,0.1

Type RM Length L Ch R = 1 ,31300   ,456.5,455.9,454.1
XS GIS Cut Line= 3
2282019.70320733 622918.876202982282140.79994457622925.054607941
 2282673.3784522622706.339072324
#Sta/Elev= 30
       0 2714.73    24.5 2712.02    40.8 2706.56    64.6 2687.95    92.6 2662.44
   120.6 2643.47   133.6  2637.7   152.5 2633.74   166.7  2625.8   181.1 2619.73
     220 2593.98   234.1 2591.85     246 2586.41   270.9 2584.32   283.1 2582.98
   295.12584.328   310.7 2595.79   356.7 2616.36   393.5 2635.05   414.6 2641.26
   479.5 2664.82   510.5 2680.95     521 2683.84   534.5 2692.86   557.3 2703.85
   570.3 2711.76   580.5 2714.13   609.2 2729.99   639.5  2743.2     697 2771.23
#Mann= 3 ,-1,0
       0      .1       0   270.9    .045       0   295.1      .1       0
Bank Sta=270.9,295.1
XS Rating Curve= 0 ,0
Exp/Cntr(USF)=0,0
Exp/Cntr=0.3,0.1

Type RM Length L Ch R = 1 ,30844   ,476.1,485.2,492.2
XS GIS Cut Line= 2
2282179.17239191623439.8092506522282904.10524065623044.391333153
#Sta/Elev= 30
       0 2697.38    10.3 2697.11    55.8 2690.78    87.7 2684.39   146.9 2662.64
   197.1 2646.21   247.4 2625.25   273.9 2600.64   283.6 2593.12   297.3 2584.54
     311 2578.32   320.1 2571.46   329.9  2569.7   339.6 2568.68   348.92569.698
   359.4 2571.34   374.2 2567.74   397.7 2575.55   418.4 2578.28     442 2592.51
   456.7 2604.65   481.6 2617.09   520.6 2630.23   584.4 2658.85   606.9 2672.22
   618.9 2676.72   675.5 2709.18   730.2 2735.92   772.2 2758.39   825.8  2789.4
#Mann= 3 ,-1,0
       0      .1       0   329.9    .045       0   348.9      .1       0
Bank Sta=329.9,348.9
XS Rating Curve= 0 ,0
Exp/Cntr(USF)=0,0
Exp/Cntr=0.3,0.1

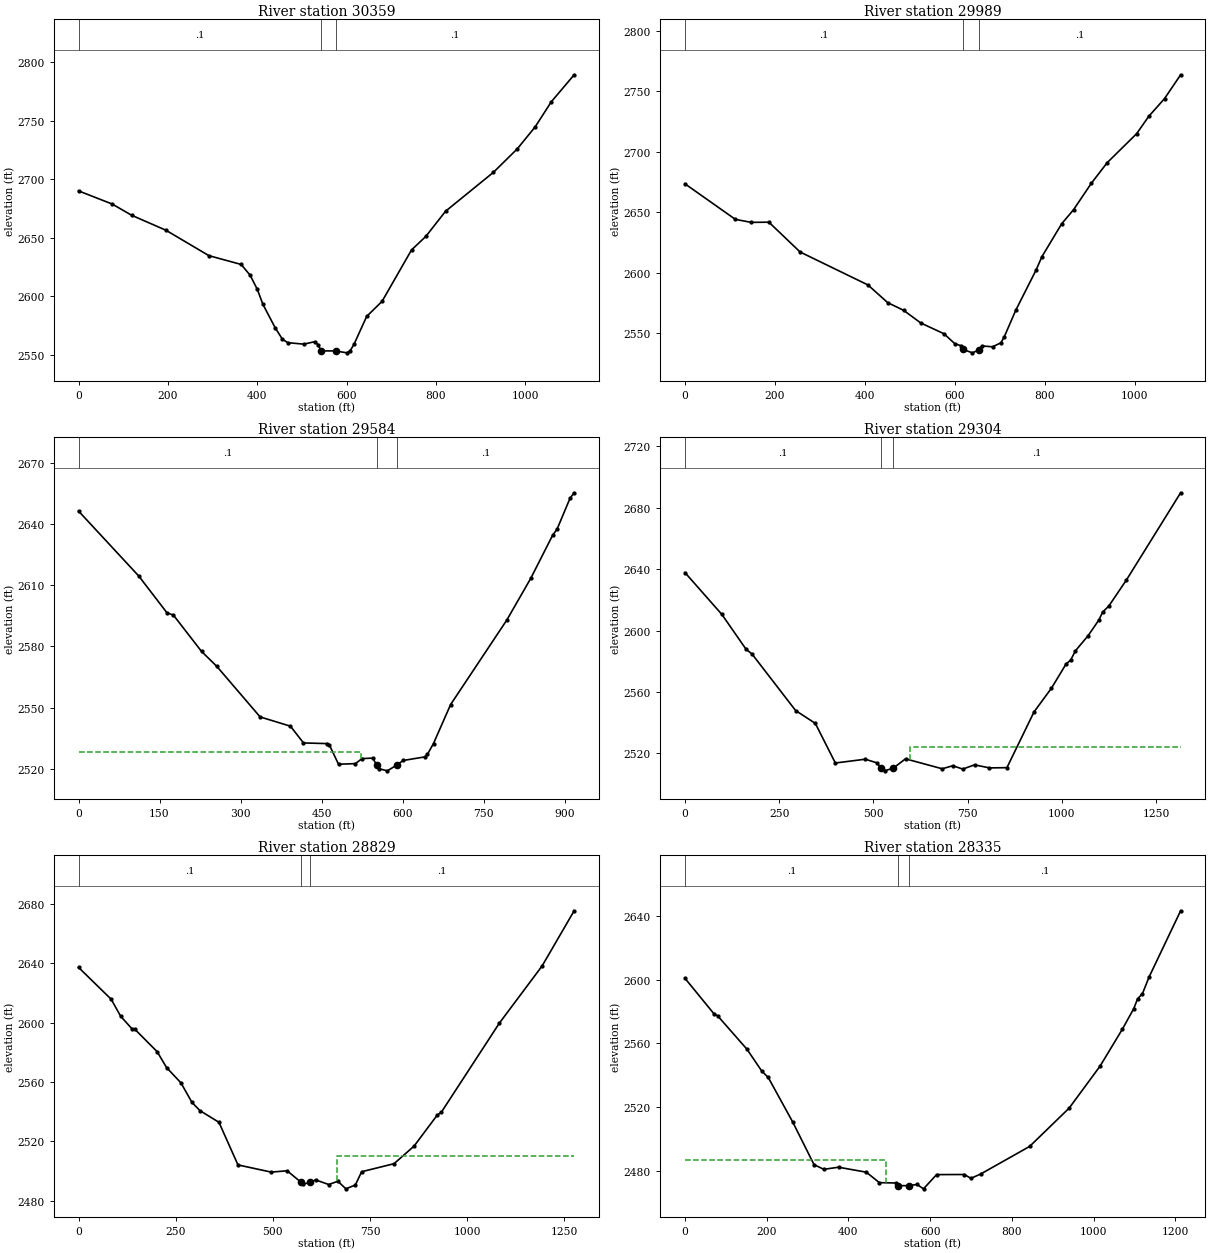
Type RM Length L Ch R = 1 ,30359   ,374.5,369.6,363
XS GIS Cut Line= 2
2282189.09525619623674.231426097 2283295.1060208623590.327161196
#Sta/Elev= 30
       0 2690.14    75.3 2678.89   119.4 2669.18   195.6 2656.47   291.9 2634.69
   364.1 2627.18   384.2 2617.88   400.2 2605.84   412.3 2593.37   440.3 2572.85
   456.4 2563.18   468.4 2560.24   504.5 2559.02   528.6 2561.12   536.6 2558.35
   542.62553.244   575.2  2553.2   600.8 2551.57   607.9 2553.29   616.8 2559.11
   644.9 2582.74   679.4 2595.67   745.2 2639.59   777.3  2651.2   821.4 2672.71
   928.6 2706.03   981.9 2726.09    1022 2744.93  1058.1 2766.39  1109.2 2789.46
#Mann= 3 ,-1,0
       0      .1       0   542.6    .045       0   575.2      .1       0
Bank Sta=542.6,575.2
XS Rating Curve= 0 ,0
Exp/Cntr(USF)=0,0
Exp/Cntr=0.3,0.1

Type RM Length L Ch R = 1 ,29989   ,398.9,405.7,411.3
XS GIS Cut Line= 2
 2282310.2245967624234.6298842832283312.58788611623775.785239289
#Sta/Elev= 30
       0 2673.53   112.1 2644.17   147.3 2641.69   186.6 2641.85   256.1  2617.2
   406.9 2589.99   450.9 2575.36   486.1 2569.06   524.6 2558.53   575.9 2549.69
   600.4 2541.37   613.6 2539.83     618 2536.75   639.3 2533.89   653.2 2536.23
   660.4 2539.61     684 2538.88   702.7 2542.19   710.4 2547.37   735.9 2569.23
   780.8 2602.22     794 2613.44     838 2640.62   864.4 2652.23     904  2674.1
   939.2 2691.07  1004.5 2714.95  1031.6 2729.34  1066.7    2744  1102.4 2763.64
#Mann= 3 ,-1,0
       0      .1       0     618    .045       0   653.2      .1       0
Bank Sta=618,653.2
XS Rating Curve= 0 ,0
Exp/Cntr(USF)=0,0
Exp/Cntr=0.3,0.1

Type RM Length L Ch R = 1 ,29584   ,266.1,279.2,287.9
XS GIS Cut Line= 2
2282409.00468284624409.4031272532283323.76659164624334.043079427
#Sta/Elev= 30
       0 2646.31   111.5 2614.48   163.7 2596.47   175.8 2595.28   227.9 2577.48
     256 2570.21   336.3  2545.4   392.5 2540.85   416.6 2532.65   460.7 2532.32
   464.7 2531.57   481.5 2522.21   512.9 2522.51   524.9 2524.97     545 2525.22
   552.12521.772   557.1 2519.98   571.8 2518.97     589 2521.73   601.2 2524.05
   641.3  2525.8   646.2 2527.06   657.4 2532.37   689.1 2551.46     793 2592.81
   837.5 2613.31     878 2634.43   886.2 2637.41   910.2 2652.54   917.9 2655.26
#Mann= 3 ,-1,0
       0      .1       0   552.1    .045       0     589      .1       0
#XS Ineff= 2 , 0
          523.47  2528.4
Permanent Ineff=
       F       F
Bank Sta=552.1,589
XS Rating Curve= 0 ,0
Exp/Cntr(USF)=0,0
Exp/Cntr=0.3,0.1

Type RM Length L Ch R = 1 ,29304   ,483.4,475.4,468.1
XS GIS Cut Line= 4
 2282398.1901369624551.6340436382282786.19396844624547.927000662
2283186.55460991624783.9420701692283623.98568114624633.188989123
#Sta/Elev= 30
       0 2637.77      98 2610.47     162 2587.85     178 2584.69   293.6 2547.88
     346 2539.48   399.1 2513.67   478.5 2516.15   510.2 2513.71   519.72510.275
   529.6 2508.57   552.72510.287   585.3  2516.4   682.8 2509.91   710.7  2511.9
   737.1 2509.73   768.6 2512.47   808.2 2510.49   854.5 2510.64   926.4 2546.97
   972.6 2562.41    1011 2578.03  1023.7  2580.8  1036.4 2586.83    1070 2596.67
  1098.5 2606.86  1108.3 2611.94  1125.3 2616.11  1171.8 2633.01  1315.5 2689.78
#Mann= 3 ,-1,0
       0      .1       0   519.7    .045       0   552.7      .1       0
#XS Ineff= 2 , 0
                          598.41         2523.96
Permanent Ineff=
       F       F
Bank Sta=519.7,552.7
XS Rating Curve= 0 ,0
Exp/Cntr(USF)=0,0
Exp/Cntr=0.3,0.1

Type RM Length L Ch R = 1 ,28829   ,494.1,493.7,490.6
XS GIS Cut Line= 4
2282433.85199203624945.3467552692283031.77771562 625065.10069646
 2283219.3639264625026.5942448892283636.81508322624801.909322842
#Sta/Elev= 30
       0 2637.38      84  2615.9   108.4 2604.45     137 2596.12   145.1 2595.61
   202.4 2580.52   226.7 2569.79   263.5 2559.53     292  2546.3   312.4  2540.8
   361.4 2532.91   410.3 2504.18     496 2499.32   536.8 2500.24   571.42492.754
   577.6 2491.22   595.72492.376   610.2 2494.06   643.9 2490.97   667.4 2493.16
     688 2488.05   712.3 2490.64   728.6 2499.59   811.8 2504.99   863.4 2516.85
   922.4 2537.54     934 2539.86  1082.8 2599.73  1192.9 2638.33  1275.4 2675.53
#Mann= 3 ,0,0
       0      .1       0   571.4    .045       0   595.7      .1       0
#XS Ineff= 2 , 0
                          665.95            2510
Permanent Ineff=
       F       F
Bank Sta=571.4,595.7
XS Rating Curve= 0 ,0
Exp/Cntr(USF)=0,0
Exp/Cntr=0.3,0.1

Type RM Length L Ch R = 1 ,28335   ,619.8,618.7,601.5
XS GIS Cut Line= 3
 2282580.4369804625463.6072967262283316.35366019625452.623465685
2283726.87434537625209.606203888
#Sta/Elev= 30
       0 2600.79    71.7 2578.27    79.7  2577.3   151.8  2556.2   187.8 2542.55
   203.8 2538.47   263.8 2510.43   315.8 2483.72   339.8 2480.75   375.8 2482.08
   443.8 2478.95   475.8 2472.38   515.8 2472.17   520.5 2470.49   547.8 2470.48
   567.8 2471.25   583.8 2468.49   615.8 2477.43   683.8  2477.5   699.8 2475.09
   723.8 2477.82   843.5 2495.14   940.3 2519.23  1015.8 2545.57  1070.5 2568.82
  1098.4 2581.76  1107.7 2587.89  1119.7 2591.17  1135.5 2601.42  1213.1 2643.24
#Mann= 3 ,-1,0
       0      .1       0   520.5    .045       0   547.8      .1       0
#XS Ineff= 2 , 0
          492.17 2486.67
Permanent Ineff=
       F       F
Bank Sta=520.5,547.8
XS Rating Curve= 0 ,0
Exp/Cntr(USF)=0,0
Exp/Cntr=0.3,0.1

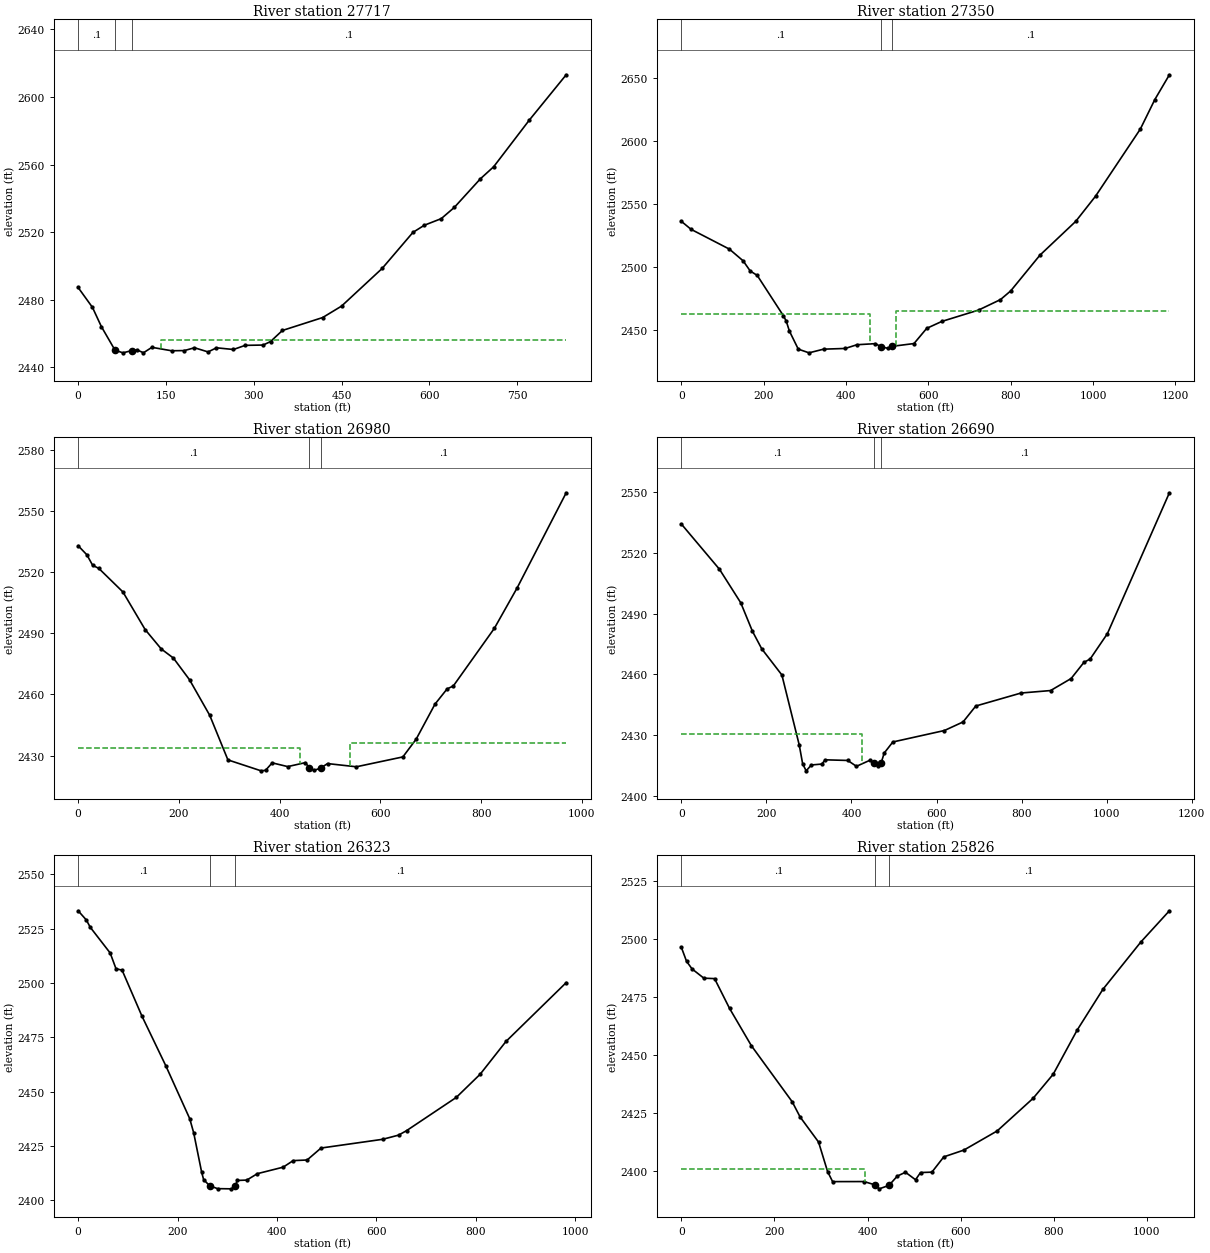
Type RM Length L Ch R = 1 ,27717   ,366.3,366.2,353.5
XS GIS Cut Line= 2
2283155.04122181626035.3923197782283850.53129534625575.799464166
#Sta/Elev= 30
       0 2487.24    24.5 2475.45    39.7 2464.08      63 2450.11    76.6 2448.55
    91.9 2449.92   100.6 2450.28   111.6 2448.59     126 2451.81   159.6 2449.78
   181.4 2449.89   198.7 2451.56   221.9  2449.1   236.3 2451.53   265.2 2450.53
   285.3 2452.98     316 2453.16   328.6 2455.23   348.8 2461.78   417.6 2469.44
   449.9 2476.22   519.2  2498.5   571.9 2519.89   591.3  2524.1   620.2 2528.01
   642.5 2534.65     687 2551.58   709.7 2558.72   770.3 2586.22   833.6 2613.19
#Mann= 3 ,-1,0
       0      .1       0      63    .045       0    91.9      .1       0
#XS Ineff= 2 , 0
                          141.52         2455.98
Permanent Ineff=
       F       F
Bank Sta=63,91.9
XS Rating Curve= 0 ,0
Exp/Cntr(USF)=0,0
Exp/Cntr=0.3,0.1

Type RM Length L Ch R = 1 ,27350   ,361.4,370.5,376.6
XS GIS Cut Line= 4
2283156.05413834626521.7163537382283389.90125724626360.620165128
2283667.24299105625934.9967122642284011.03012251625744.050945776
#Sta/Elev= 30
       0 2536.22    23.5 2529.89   116.7  2514.2     150 2504.96   167.3 2496.89
   184.3 2493.39   247.9 2461.43   254.8 2457.19   262.4 2449.37     284 2435.02
   310.1  2432.1   345.4 2435.01   397.9 2435.57   426.5 2438.52   471.3 2439.38
   483.92437.092     502 2435.62   510.7  2437.2     565 2439.45   595.9 2451.49
   632.5 2456.96   721.7 2465.95     775 2474.25   799.9 2481.15   870.8 2509.41
   957.8 2536.19  1005.8 2556.08  1114.6 2609.22  1149.9 2632.64  1185.2 2652.21
#Mann= 3 ,-1,0
       0      .1       0   483.9    .045       0   510.7      .1       0
#XS Ineff= 2 , 0
          459.02  2463.2  520.22          2465.6
Permanent Ineff=
       F       F
Bank Sta=483.9,510.7
XS Rating Curve= 0 ,0
Exp/Cntr(USF)=0,0
Exp/Cntr=0.3,0.1

Type RM Length L Ch R = 1 ,26980   ,285.3,290,298.2
XS GIS Cut Line= 3
2283199.36229931626593.568915136 2283495.3155246626578.313594245
2284107.05389234626299.141221936
#Sta/Elev= 30
       0 2532.95    17.3 2528.51    28.9 2523.31    40.9 2521.86    88.9 2510.27
     133 2491.82     165  2482.3   189.1 2477.84   221.1  2467.2   261.2 2449.76
   297.3 2427.88   363.2 2422.51     372 2422.76   385.2 2426.43     416 2424.59
   451.2 2426.54   458.72423.998   468.8 2422.75     482 2423.96     482 2423.98
   495.1 2426.07   552.3  2424.5   644.6 2429.34     671 2438.06   708.4 2455.25
   732.5 2462.73   744.7 2464.13   826.2 2492.42   871.5 2512.29   968.8 2558.92
#Mann= 3 ,-1,0
       0      .1       0   458.7    .045       0     482      .1       0
#XS Ineff= 2 , 0
           440.8 2433.81  539.16         2436.05
Permanent Ineff=
       F       F
Bank Sta=458.7,482
XS Rating Curve= 0 ,0
Exp/Cntr(USF)=0,0
Exp/Cntr=0.3,0.1

Type RM Length L Ch R = 1 ,26690   ,382.8,367.1,355.7
XS GIS Cut Line= 3
2283216.14315229626703.407225552 2283762.2836402626810.194471791
2284114.68155279626335.753992075
#Sta/Elev= 30
       0 2534.25    89.7  2511.9   139.7 2495.37   167.1 2481.34     189 2472.65
   236.4 2459.72   277.2 2425.17   285.3 2415.81   293.5 2412.39   305.7 2415.28
   330.2 2415.74   338.3 2417.83   391.3 2417.52   411.7 2414.62   444.3  2417.7
   452.4 2416.02   461.8 2414.72   469.62416.138   476.9 2421.16   497.3 2426.64
   618.6  2432.3   662.4 2436.53   692.3 2444.39   798.7 2450.81   868.2 2452.03
   916.5 2457.97   946.4 2465.91   961.3 2467.63  1001.7 2480.11  1147.5 2549.67
#Mann= 3 ,-1,0
       0      .1       0   452.4    .045       0   469.6      .1       0
#XS Ineff= 2 , 0
          424.04 2430.72
Permanent Ineff=
       F       F
Bank Sta=452.4,469.6
XS Rating Curve= 0 ,0
Exp/Cntr(USF)=0,0
Exp/Cntr=0.3,0.1

Type RM Length L Ch R = 1 ,26323   ,518.7,496.4,482.2
XS GIS Cut Line= 2
2283215.80414516627007.8356291142284197.22978916627026.989532011
#Sta/Elev= 30
       0 2533.16    16.4 2528.96    24.4 2525.57    64.4 2513.76    76.2 2506.49
    88.4 2505.86   128.4 2484.69   176.4 2461.85   224.4 2437.58   232.4 2431.06
   248.4 2412.97   252.4 2409.53   264.4 2406.73   280.4 2405.38   308.4 2405.29
   315.6 2406.65   320.4 2409.16   339.2 2409.31   360.4 2412.26   412.4 2415.26
   432.5 2418.27   460.5 2418.55   488.5 2424.05   612.5 2428.07   644.5 2429.99
   660.5 2432.04   760.5 2447.32   808.5 2457.98   860.5 2473.07   981.6 2500.12
#Mann= 3 ,-1,0
       0      .1       0   264.4    .045       0   315.6      .1       0
Bank Sta=264.4,315.6
XS Rating Curve= 0 ,0
Exp/Cntr(USF)=0,0
Exp/Cntr=0.3,0.1

Type RM Length L Ch R = 1 ,25826   ,608.3,618.2,621.1
XS GIS Cut Line= 3
2283456.66871168627706.0584826932283970.77302571627138.560545541
2284248.41986593627085.166922422
#Sta/Elev= 30
       0 2496.29    11.2 2490.24    23.1 2486.93    48.4 2482.96    71.4 2482.77
   103.7 2469.89   150.4 2453.87   238.2 2429.67   255.1 2423.14   294.8  2412.3
   314.2 2399.58     325 2395.24   392.5 2395.27   416.8  2393.8   425.1 2392.13
   446.1 2393.62     464 2397.63   481.5 2399.28   503.1 2396.05   513.9 2399.15
   538.3 2399.33   563.8 2405.91     607 2408.84   678.5 2417.09   755.9  2431.2
   798.9 2441.55   850.1 2460.49   905.7 2478.17   987.1 2498.54  1048.5 2512.02
#Mann= 3 ,-1,0
       0      .1       0   416.8    .045       0   446.1      .1       0
#XS Ineff= 2 , 0
          395.09 2400.71
Permanent Ineff=
       F       F
Bank Sta=416.8,446.1
XS Rating Curve= 0 ,0
Exp/Cntr(USF)=0,0
Exp/Cntr=0.3,0.1

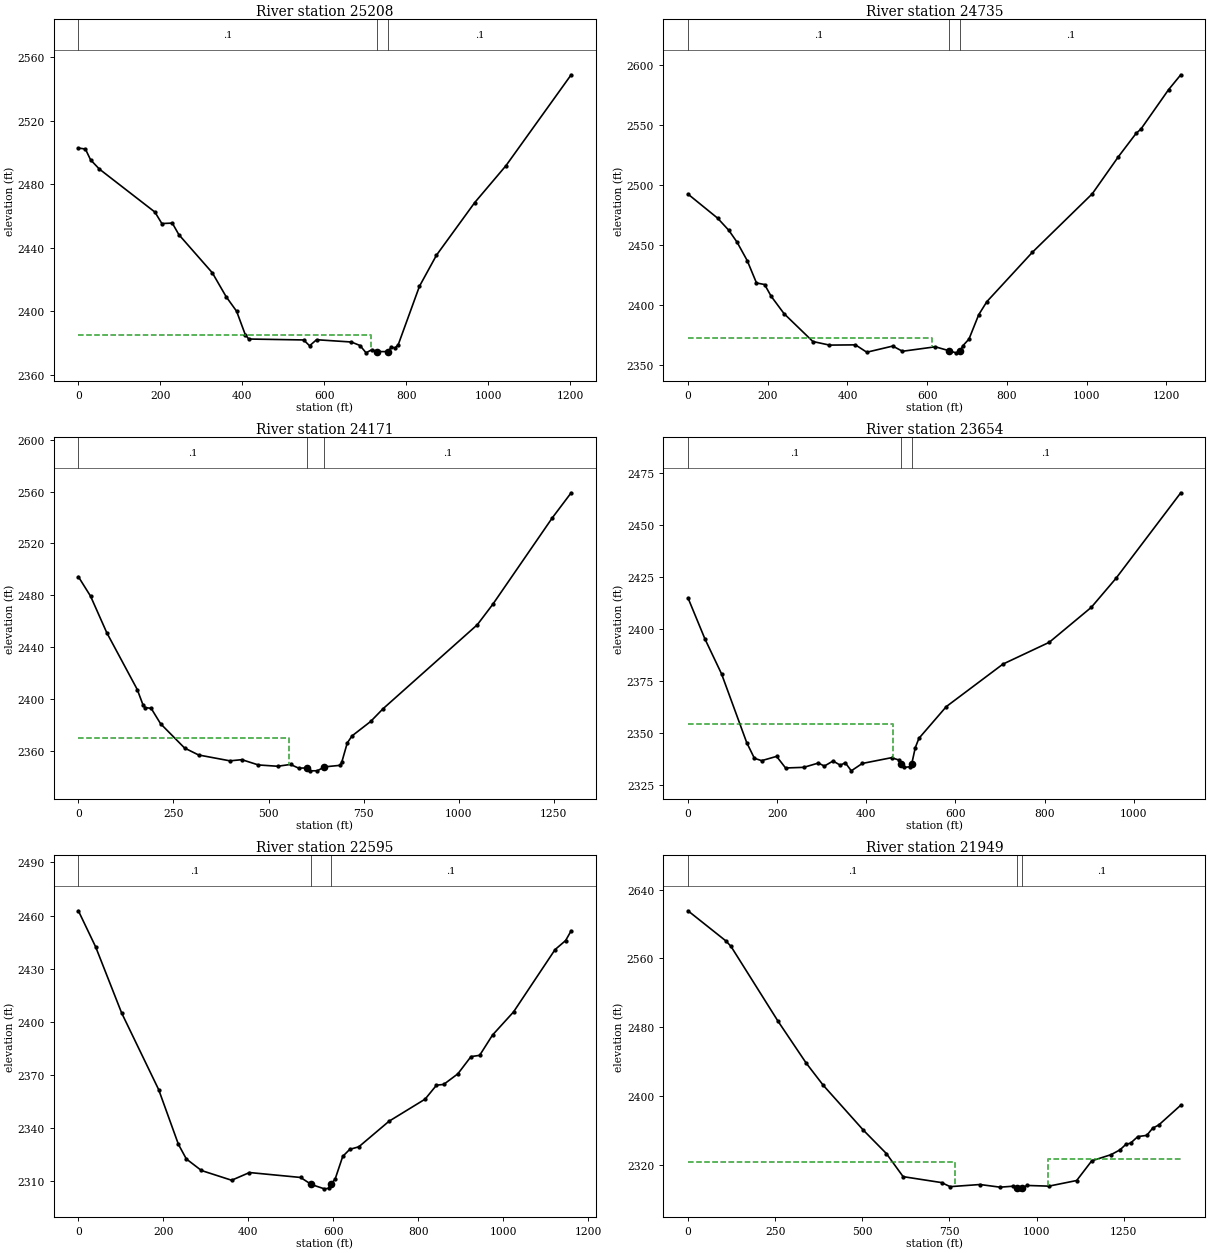
Type RM Length L Ch R = 1 ,25208   ,470.6,473.6,474.6
XS GIS Cut Line= 2
2283472.03690577627897.4621103212284606.19427867627499.602804111
#Sta/Elev= 30
       0 2502.78    17.1 2502.16    29.8 2495.34      51 2489.58   186.7 2462.44
   203.6 2455.22   229.1  2455.5   245.1 2448.21   326.7  2424.2   360.5  2409.1
   385.9 2399.99   407.1 2385.19   415.6 2382.47   549.5 2381.89   563.9 2378.21
   580.9 2382.03   665.8 2380.59   686.9 2378.39   701.7 2373.77   715.8 2375.78
   729.3 2374.57   754.7 2374.53   763.2 2377.33   772.3 2376.88   780.1 2378.87
   831.9 2415.72   873.4 2435.29   966.6 2468.41  1042.9 2491.69  1201.9 2548.93
#Mann= 3 ,-1,0
       0      .1       0   729.3    .045       0   754.7      .1       0
#XS Ineff= 2 , 0
          714.66 2384.91
Permanent Ineff=
       F       F
Bank Sta=729.3,754.7
XS Rating Curve= 0 ,0
Exp/Cntr(USF)=0,0
Exp/Cntr=0.3,0.1

Type RM Length L Ch R = 1 ,24735   ,555.1,563.7,582.2
XS GIS Cut Line= 2
2283607.23227012628227.194262418 2284822.3185791628002.025726064
#Sta/Elev= 30
       0 2492.78    74.2 2472.75   102.7 2462.47     123 2452.74   148.5 2437.38
   171.8 2418.68   192.2 2417.36   208.6 2407.59     241 2393.06   313.2 2369.86
   354.9 2366.86     420 2367.06   448.4 2360.93   513.5 2366.05   537.9 2361.72
   620.3 2365.45   654.6 2362.18   672.2 2360.41   682.8 2361.77     689 2366.17
   704.7 2371.91   729.1  2392.2   749.5 2403.09   863.4 2444.18  1013.9 2493.04
    1079 2523.79  1123.8 2543.42    1136 2547.05  1205.1 2579.81  1235.8 2592.26
#Mann= 3 ,-1,0
       0      .1       0   654.6    .045       0   682.8      .1       0
#XS Ineff= 2 , 0
          612.56 2372.93
Permanent Ineff=
       F       F
Bank Sta=654.6,682.8
XS Rating Curve= 0 ,0
Exp/Cntr(USF)=0,0
Exp/Cntr=0.3,0.1

Type RM Length L Ch R = 1 ,24171   ,519.5,516.7,502.6
XS GIS Cut Line= 4
2283632.82249544  628315.47695092283986.23544336628607.452974097
 2284262.6359882628702.2012168722284799.09366094628606.145431692
#Sta/Elev= 30
       0 2494.34      32 2479.34    74.6 2451.12   154.8  2407.2   170.4 2394.93
   175.6 2393.27   191.4 2392.63   216.2 2380.74   279.3 2361.98   316.1 2356.62
   398.5 2352.09   429.8    2353   473.2 2348.92   523.9 2347.91   557.7 2349.31
   578.9 2346.48   599.9 2346.59   608.5 2344.37   628.2 2344.42646.91072347.439
   688.8 2348.64     693 2351.56   706.9  2365.9   719.5 2371.37   768.4  2382.5
   800.9 2392.31  1048.8 2457.22  1089.5    2473  1246.2  2539.9  1295.6 2559.17
#Mann= 3 ,-1,0
       0      .1       0   599.9    .045       0646.9107      .1       0
#XS Ineff= 2 , 0
          553.37  2369.6
Permanent Ineff=
       F       F
Bank Sta=599.9,646.9107
XS Rating Curve= 0 ,0
Exp/Cntr(USF)=0,0
Exp/Cntr=0.3,0.1

Type RM Length L Ch R = 1 ,23654   ,1037.2,1058.7,1062.4
XS GIS Cut Line= 3
2283542.73637273628965.1851636172284252.14018372629124.225546022
2284616.25895396629021.686352103
#Sta/Elev= 30
       0 2415.04      38 2395.34    75.3 2378.56   131.8 2345.54     149 2338.03
   165.3  2336.9   198.8 2338.95   218.9 2333.38   259.7 2333.69   292.5 2335.75
   305.9 2334.29   325.3 2336.73   341.7 2334.72   352.8  2335.9   366.3 2332.01
   390.9 2335.55   456.5 2338.32   472.9 2337.22   477.5 2335.46   485.2 2333.65
   497.5 2333.98     502 2335.47   509.8 2343.12     518 2347.61   579.5 2362.86
   706.6 2383.26   810.2 2393.69   904.6 2410.48   959.8 2424.36  1105.3 2465.47
#Mann= 3 ,-1,0
       0      .1       0   477.5    .045       0     502      .1       0
#XS Ineff= 2 , 0
          459.02 2354.56
Permanent Ineff=
       F       F
Bank Sta=477.5,502
XS Rating Curve= 0 ,0
Exp/Cntr(USF)=0,0
Exp/Cntr=0.3,0.1

Type RM Length L Ch R = 1 ,22595   ,651.4,646.7,642.7
XS GIS Cut Line= 2
2283139.33631489629380.9287256912283852.68959273630295.054782151
#Sta/Elev= 30
       0 2462.75    40.7 2442.35   101.8 2405.09   188.9 2361.84   235.4 2330.94
     254  2322.7   289.5 2316.18   360.6 2310.68   402.6 2315.03   522.9 2312.25
548.09992308.297   578.7 2305.83   588.9 2306.12   593.72308.367   604.1 2311.32
     622 2324.14   638.5 2328.11   659.9 2329.56   730.9 2343.97   815.8 2356.45
   842.6 2364.31   859.6 2364.77   892.8 2370.72   923.8 2380.46   944.1 2381.16
   974.5 2392.64  1023.9 2405.67  1121.6 2440.85  1146.4 2445.94  1159.5 2451.47
#Mann= 3 ,-1,0
       0      .1       0548.0999    .045       0   593.7      .1       0
Bank Sta=548.0999,593.7
XS Rating Curve= 0 ,0
Exp/Cntr(USF)=0,0
Exp/Cntr=0.3,0.1

Type RM Length L Ch R = 1 ,21949   ,884.3,888.4,887.1
XS GIS Cut Line= 3
 2282253.0859808629762.7710283532283202.09840249630389.349998252
2283297.81166055630648.789463917
#Sta/Elev= 30
       0  2615.4   109.2  2580.2   123.5  2573.9   258.5  2486.8   339.2 2438.15
   387.9 2412.45   503.4 2360.04   569.3 2332.88   617.2 2306.07   727.5 2299.15
   752.1 2294.42   837.7 2296.91   895.2 2293.82   933.6 2294.97   945.1 2292.64
   952.8 2291.88   959.6 2292.61   971.9 2295.82  1035.3 2295.02  1115.1 2301.57
  1158.3 2324.46  1213.8 2331.66  1239.3 2337.24  1256.4  2343.7  1269.5 2345.01
  1290.5 2352.67  1316.1 2354.08  1333.1  2362.5  1350.5 2366.14  1413.7 2389.21
#Mann= 3 ,-1,0
       0      .1       0   945.1    .045       0   959.6      .1       0
#XS Ineff= 2 , 0
          766.48  2323.6 1031.69          2326.8
Permanent Ineff=
       F       F
Bank Sta=945.1,959.6
XS Rating Curve= 0 ,0
Exp/Cntr(USF)=0,0
Exp/Cntr=0.3,0.1

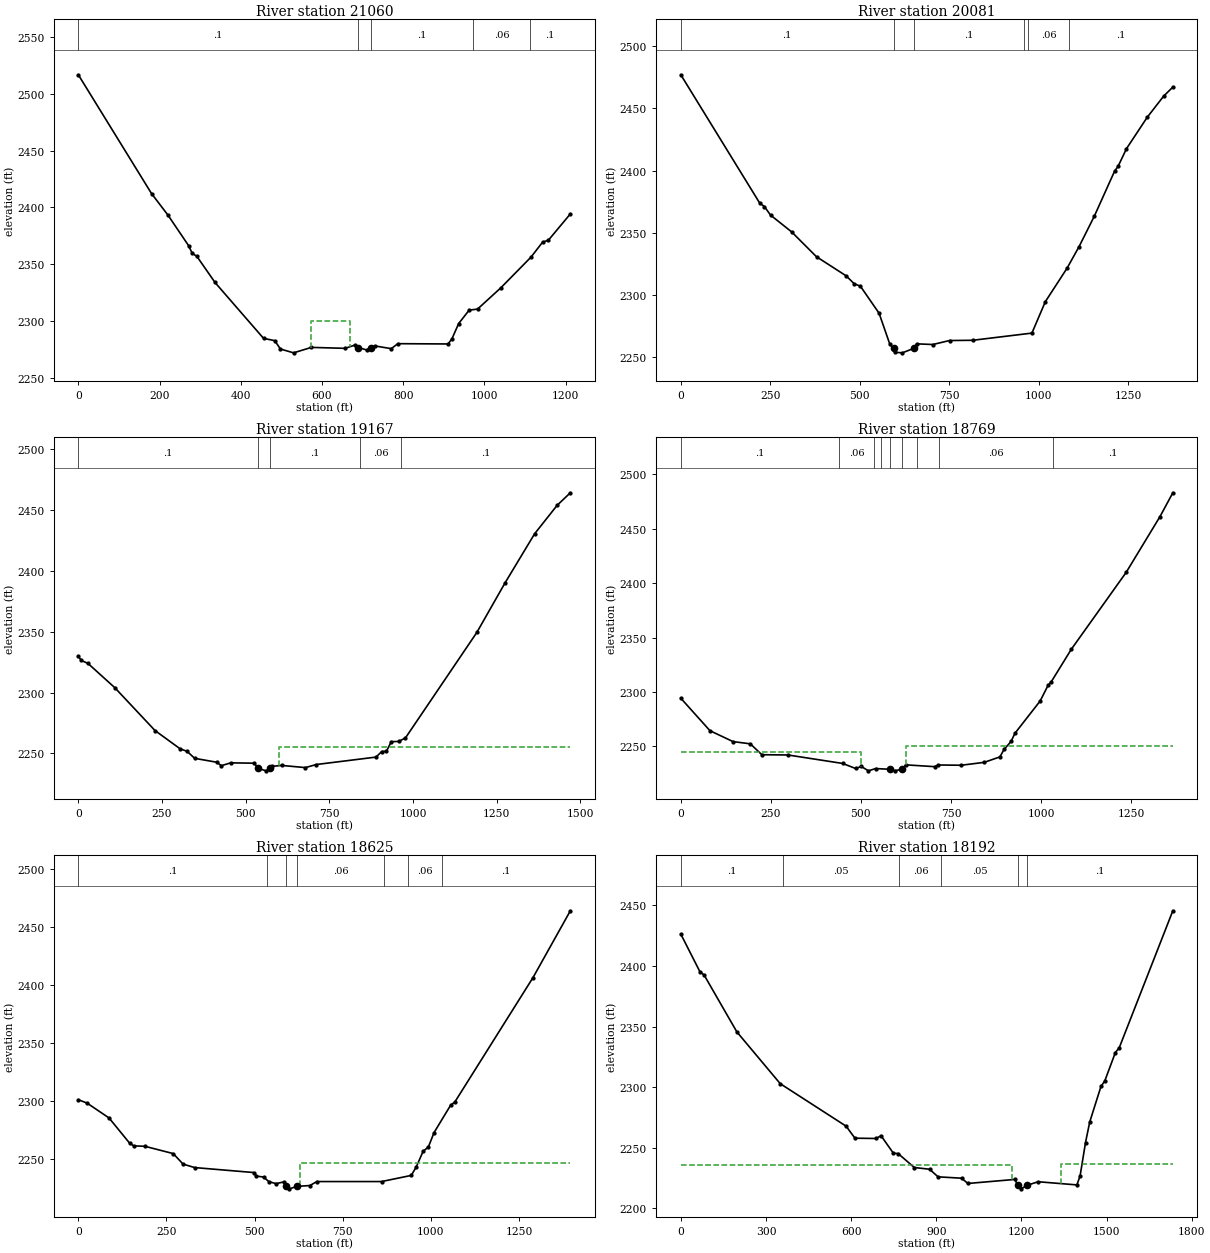
Type RM Length L Ch R = 1 ,21060   ,989,979.4,955.7
XS GIS Cut Line= 4
2281973.44971016630196.0756983332282335.97409811630540.301224702
2282577.80946256630887.1393535242282779.86085475631094.026984687
#Sta/Elev= 30
       0 2516.75   180.3 2412.25   220.6 2393.37   271.5 2366.47   280.4 2359.76
   292.1 2356.95   336.6 2334.06   456.1  2284.9   483.8 2282.84   497.8 2275.48
   530.2 2272.13   574.1 2276.92     657 2276.09   681.4 2278.98   689.1 2276.82
   710.1 2274.69   720.62276.824   730.2 2278.21   770.8 2275.82     787 2280.19
   910.6 2279.94   920.2 2284.43   936.8 2297.91   962.6 2309.67   983.4 2310.64
  1040.6 2329.32    1115 2356.37  1143.6 2369.53  1157.8  2371.2  1211.9 2394.35
#Mann= 5 ,-1,0
       0      .1       0   689.1    .045       0   720.6      .1       0
  972.74     .06       0 1112.74      .1       0
#XS Ineff= 1 ,-1
  573.14  669.17 2300.15
Permanent Ineff=
       F
Bank Sta=689.1,720.6
XS Rating Curve= 0 ,0
Exp/Cntr(USF)=0,0
Exp/Cntr=0.3,0.1

Type RM Length L Ch R = 1 ,20081   ,911.8,913.8,910.4
XS GIS Cut Line= 3
2281273.28630221630732.4579202572282054.11935029631333.555873834
2282261.88458019631662.634606609
#Sta/Elev= 30
       0 2477.03   220.7 2373.68   233.6 2371.01   250.7 2364.13   309.4  2350.7
   379.1 2330.64   461.8  2315.3   484.6 2308.87   501.7 2306.96   553.9 2285.21
   584.2 2260.07   594.3 2256.99   599.3 2253.75   618.7 2253.33   651.52256.972
   658.6 2260.57   704.2 2260.03   750.7 2263.23   815.5 2263.43   980.9 2269.21
  1018.5 2294.54  1079.2 2321.47  1112.7 2338.81  1155.3  2363.3    1212 2399.57
  1221.5 2403.28  1245.1 2417.57  1302.7 2442.69  1348.9 2459.83  1374.6 2467.13
#Mann= 6 ,-1,0
       0      .1       0   594.3    .045       0   651.5      .1       0
     960     .07       0     970     .06       0  1085.4      .1       0
Bank Sta=594.3,651.5
XS Rating Curve= 0 ,0
Exp/Cntr(USF)=0,0
Exp/Cntr=0.3,0.1

Type RM Length L Ch R = 1 ,19167   ,400.8,398.6,393.2
XS GIS Cut Line= 4
2281049.81735397631340.3199588472281051.32042304631672.717727814
2281570.29430247632076.5965936582281593.31330518632555.810377483
#Sta/Elev= 30
       0  2329.7     8.9  2326.4    28.9 2323.89   108.9 2304.01   228.9 2268.86
   303.9 2253.87   324.9 2251.74   347.6 2246.01   413.1 2242.83   427.4 2239.98
   455.1  2242.3   526.1 2242.03   536.2 2237.81   561.6 2235.75572.79942237.805
   578.5 2239.41   607.2  2240.2   678.2 2238.41   710.9 2240.94   889.2 2247.03
   906.2 2251.56   920.5 2251.85   934.8 2259.69   956.9 2259.88   977.2 2262.76
  1190.6 2349.43  1274.9 2390.12    1363 2430.32  1430.3 2453.69  1469.8 2463.99
#Mann= 5 ,-1,0
       0      .1       0   536.2    .045       0572.7994      .1       0
   842.4     .06       0   962.4      .1       0
#XS Ineff= 2 , 0
                          600.72         2255.47
Permanent Ineff=
       F       F
Bank Sta=536.2,572.7994
XS Rating Curve= 0 ,0
Exp/Cntr(USF)=0,0
Exp/Cntr=0.3,0.1

Type RM Length L Ch R = 1 ,18769   ,140.8,144.1,138.6
XS GIS Cut Line= 4
2280928.09100759631568.1667097492280936.56126472632074.633132146
2281336.25485734632367.6022576292281365.42314396632730.268741185
#Sta/Elev= 30
       0 2294.22      81 2264.38     145 2254.38     193 2252.33     225 2242.32
   297.1 2242.11   449.1 2234.32   485.1 2229.69   501.1 2231.52   520.9 2227.52
   540.8 2229.62   579.62228.969   595.3 2227.63   612.92228.943   625.1 2233.01
   704.4 2231.37   714.4 2232.91   778.8 2232.66   842.4 2235.33   885.8 2240.32
   897.3 2247.16   916.8  2254.5   927.6 2262.04   997.5 2291.65  1019.7 2306.14
  1027.8 2308.99  1083.9 2339.13  1236.4 2409.86  1330.3 2461.11  1365.9 2482.96
#Mann= 9 ,-1,0
       0      .1       0     440     .06       0  536.54      .1       0
  556.54     .06       0   579.6    .045       0   612.9     .06       0
  656.54      .1       0  716.54     .06       0  1032.1      .1       0
#XS Ineff= 2 , 0
          500.36 2244.38  624.77          2250.4
Permanent Ineff=
       F       F
Bank Sta=579.6,612.9
XS Rating Curve= 0 ,0
Exp/Cntr(USF)=0,0
Exp/Cntr=0.3,0.1

Type RM Length L Ch R = 1 ,18625   ,430.8,433,434.3
XS GIS Cut Line= 4
2280815.72822633631568.1667097492280830.82478423632104.064324165
2281230.51837685632397.0334496482281259.68666347632759.699933204
#Sta/Elev= 30
       0 2301.41      25 2298.44    87.1 2285.66   145.4 2263.96   157.1 2261.63
   189.1 2261.21   269.1 2254.95   297.1 2245.88     330 2242.89   497.2 2238.62
   505.2 2235.56   525.2 2234.74   540.7 2230.71   560.8 2229.07   582.4 2230.47
   589.4 2226.72     598 2224.56   620.9  2226.7   656.8 2227.41   676.6 2230.84
   860.1 2230.84   944.2 2236.13   958.6 2243.52   977.8 2256.86   992.9  2260.7
  1008.9 2273.06  1055.9 2296.63  1067.9 2299.44  1289.6  2406.7  1395.5 2464.27
#Mann= 7 ,-1,0
       0      .1       0  536.11     .06       0   589.4    .045       0
   620.9     .06       0  866.11      .1       0  936.11     .06       0
 1031.68      .1       0
#XS Ineff= 2 , 0
                          628.74         2247.04
Permanent Ineff=
       F       F
Bank Sta=589.4,620.9
XS Rating Curve= 0 ,0
Exp/Cntr(USF)=0,0
Exp/Cntr=0.3,0.1

Type RM Length L Ch R = 1 ,18192   ,726.9,724.7,715.1
XS GIS Cut Line= 4
2279773.99300691631647.8702729782280344.97600631 632234.07396194
2280772.70966789632620.386892529 2281011.6650006632860.803970666
#Sta/Elev= 30
       0 2426.36    67.5 2395.23    81.7 2392.74   197.6 2345.58   350.4 2302.86
   582.6 2267.77   613.5 2257.87   688.6 2257.61   705.4 2259.95   749.2 2245.39
   765.6  2245.2   822.8 2233.66   876.5 2232.23   906.5 2225.96   989.7 2224.83
  1011.3 2220.48  1176.8 2223.81    1187 2219.17  1199.5 2216.05  1220.22218.974
  1259.2 2221.91  1395.8 2219.29  1407.1 2226.92    1426 2254.26  1440.9 2271.25
  1480.4 2300.54  1493.9 2305.11  1531.2 2328.59  1544.8 2332.49  1733.7 2445.61
#Mann= 6 ,-1,0
       0      .1       0     360     .05       0     770     .06       0
  918.33     .05       0    1187    .045       0  1220.2      .1       0
#XS Ineff= 2 , 0
         1167.21    2236 1341.23         2236.24
Permanent Ineff=
       F       F
Bank Sta=1187,1220.2
XS Rating Curve= 0 ,0
Exp/Cntr(USF)=0,0
Exp/Cntr=0.3,0.1