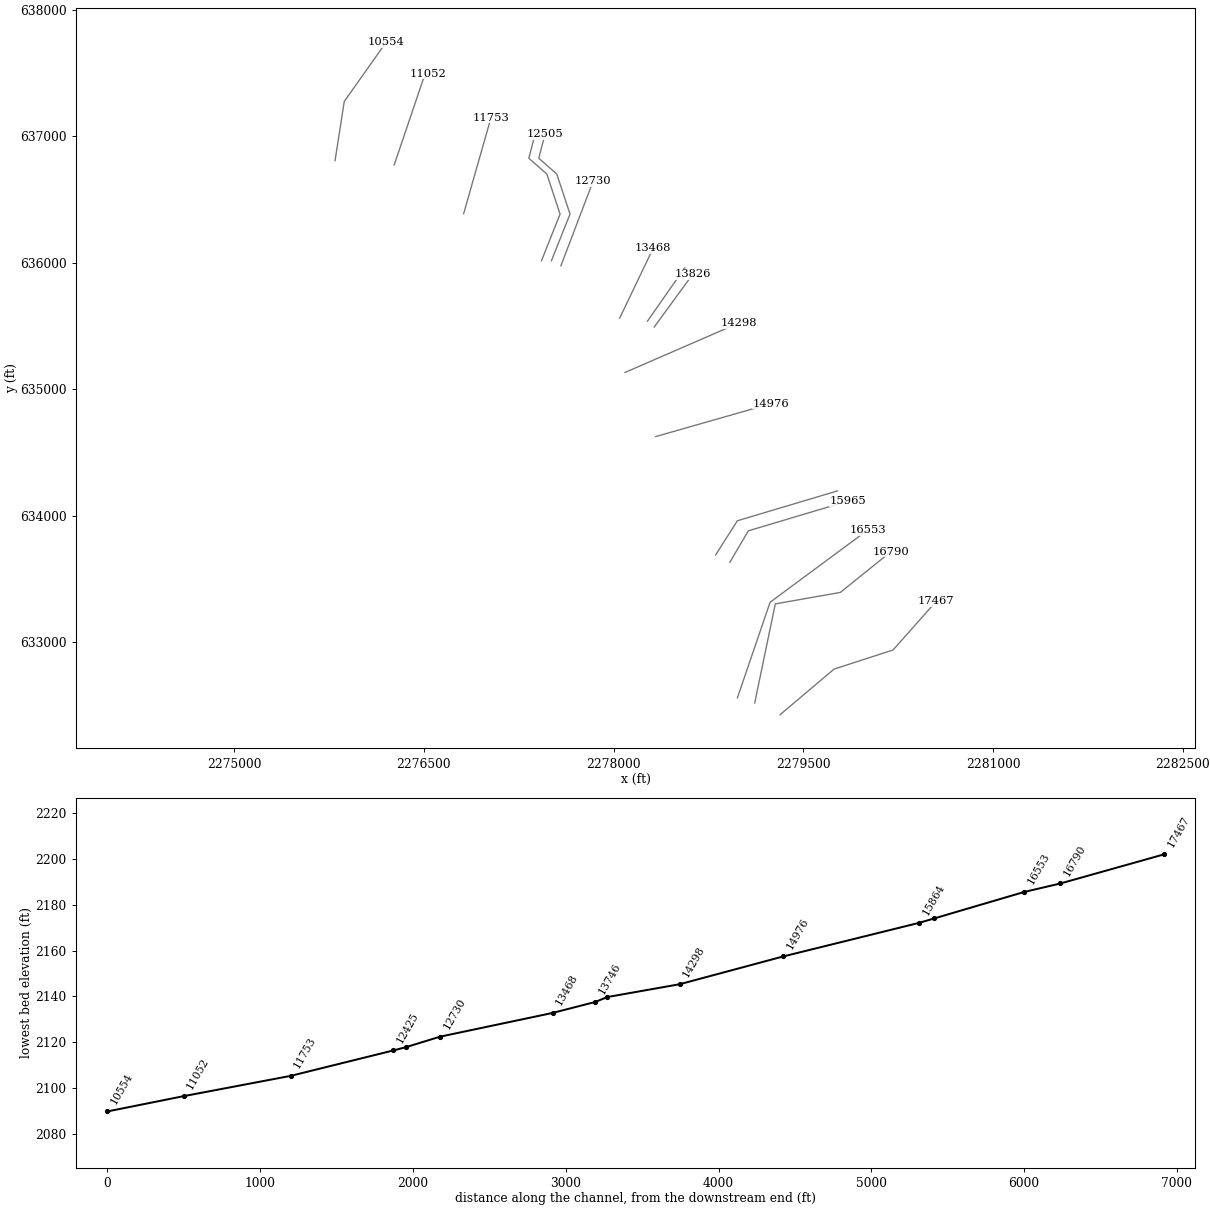
HEC-RAS study SHAVRRN.prj: SHAVRRN

--- SHAVRRN.g01 (geometry) --- (continued)

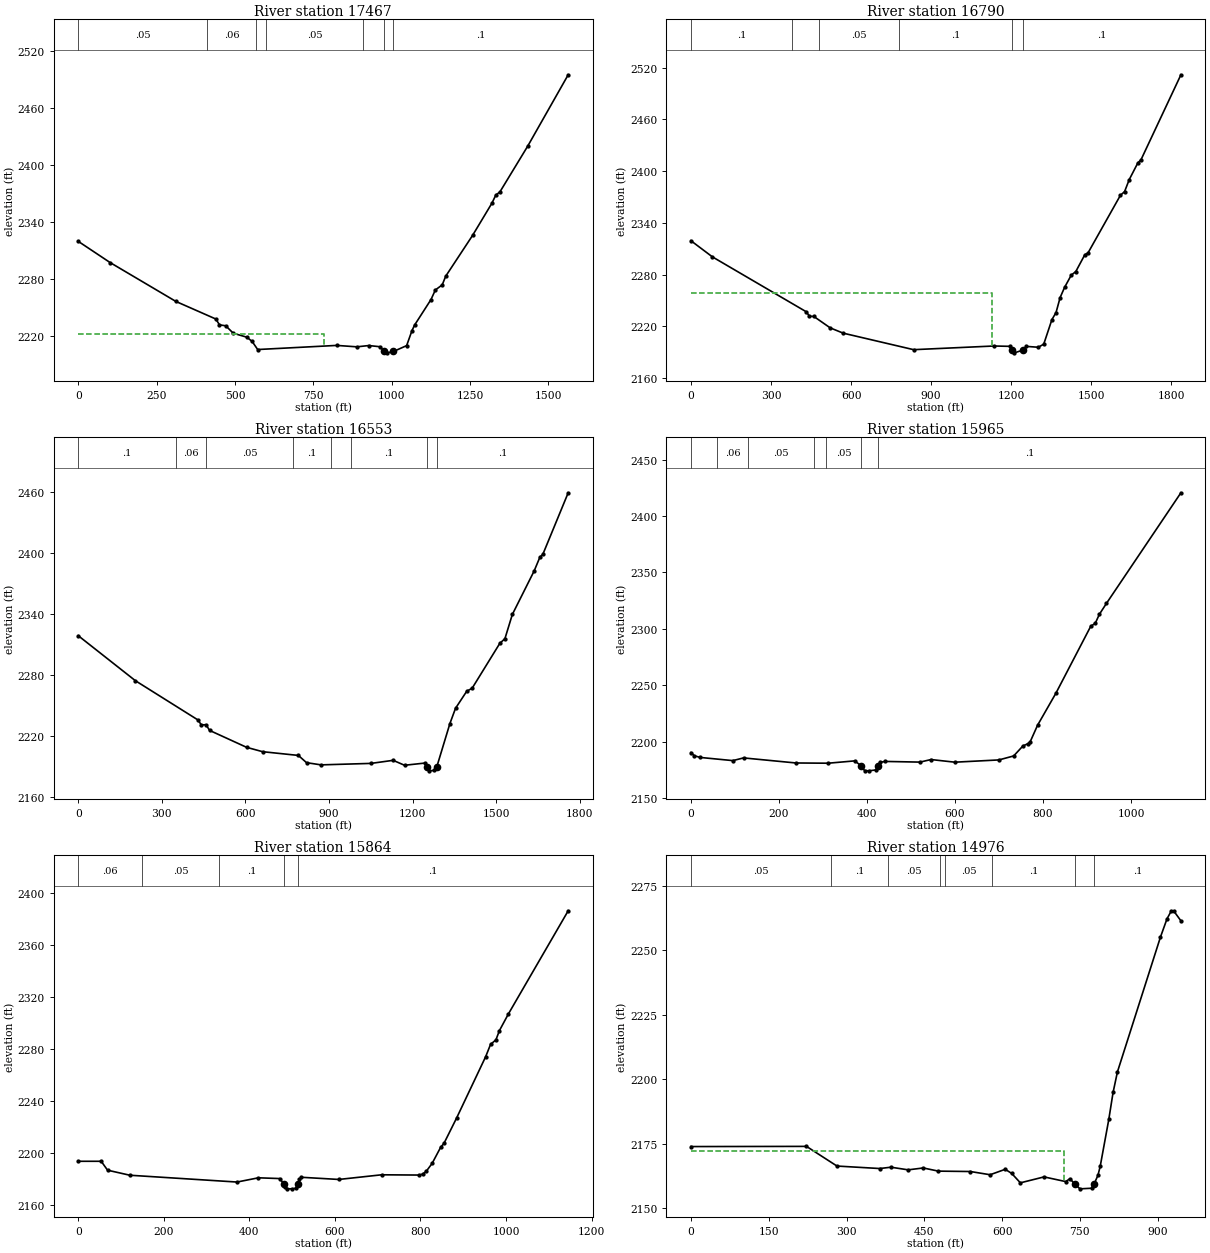
Type RM Length L Ch R = 1 ,17467   ,681.1,676.8,669.9
XS GIS Cut Line= 4
 2279316.4270004632425.9007193162279743.00962752632786.432504905
2280209.65606952632937.7565473842280550.70402337633322.053335955
#Sta/Elev= 30
       0 2319.61   101.5 2297.28   311.5 2256.26   438.9 2237.73   450.6 2231.58
   470.5 2230.59   494.6 2222.75     538 2218.56   554.8 2214.06   572.4 2205.57
   824.7 2209.91   888.7 2208.41   926.8 2209.77   963.4 2208.49   975.72203.559
   984.5 2202.08  1005.5 2203.52  1047.5 2209.67  1064.6  2225.5  1073.1 2231.44
  1125.2 2258.23  1139.2 2268.35    1161  2273.7  1172.3 2282.91  1257.8 2325.81
  1319.7 2359.87  1331.8 2368.25  1345.2 2371.77  1433.4 2419.74  1562.9 2495.16
#Mann= 7 ,-1,0
       0     .05       0     410     .06       0  568.53      .1       0
  598.53     .05       0  908.53      .1       0   975.7    .045       0
  1005.5      .1       0
#XS Ineff= 2 , 0
          783.25 2221.75
Permanent Ineff=
       F       F
Bank Sta=975.7,1005.5
XS Rating Curve= 0 ,0
Exp/Cntr(USF)=0,0
Exp/Cntr=0.3,0.1

Type RM Length L Ch R = 1 ,16790   ,230.1,237.3,246.8
XS GIS Cut Line= 4
 2279115.9440917632518.3843563022279278.70471697 633301.96050938
2279792.85809171633392.6414291722280192.54749906633714.528699978
#Sta/Elev= 30
       0 2319.31    80.5 2300.59   431.8 2237.02   444.1  2231.8   460.4 2231.55
   521.7 2218.32   570.7 2212.16   834.3 2193.05  1134.9 2197.31  1195.8  2196.9
  1203.9 2192.47  1211.8 2189.38  1242.82192.466  1256.8 2196.85  1301.4 2195.85
  1321.7 2199.46  1352.3 2227.88  1367.8 2236.12  1383.1 2253.49  1399.8 2265.26
  1424.7 2279.42  1441.8 2283.61  1475.6  2303.1  1487.3 2305.06  1609.1 2372.06
  1624.5 2376.21  1642.1 2390.27    1674 2409.36  1686.2 2413.26  1835.6 2511.66
#Mann= 6 ,-1,0
       0      .1       0     380     .06       0     480     .05       0
     780      .1       0  1203.9    .045       0  1242.8      .1       0
#XS Ineff= 2 , 0
         1129.33  2258.8
Permanent Ineff=
       F       F
Bank Sta=1203.9,1242.8
XS Rating Curve= 0 ,0
Exp/Cntr(USF)=0,0
Exp/Cntr=0.3,0.1

Type RM Length L Ch R = 1 ,16553   ,595.7,588.1,580.4
XS GIS Cut Line= 3
2278979.15953723632558.9519142862279237.50973607633314.865459037
2280009.37082396633885.787503385
#Sta/Elev= 30
       0 2318.64   205.3 2274.32   429.3 2235.81     442 2230.89   458.9 2231.01
   471.6 2225.43   604.3 2208.81   661.8  2204.5   790.2 2200.83   819.6 2193.69
   871.8 2191.53  1050.9 2192.98  1130.5    2196  1171.3 2191.14    1245 2193.32
  1252.52189.341    1260 2185.66  1278.3 2186.11    1287 2189.43  1334.3 2232.23
  1354.4 2247.18  1394.7 2263.99  1414.1 2266.96  1513.6 2311.17  1531.7 2315.65
  1558.4 2339.54  1636.8  2382.4    1657 2395.69  1667.9 2398.68  1758.9 2459.23
#Mann= 8 ,-1,0
       0      .1       0     350     .06       0     460     .05       0
     770      .1       0  908.84     .05       0  978.84      .1       0
  1252.5    .045       0    1287      .1       0
Bank Sta=1252.5,1287
XS Rating Curve= 0 ,0
Exp/Cntr(USF)=0,0
Exp/Cntr=0.3,0.1

Type RM Length L Ch R = 1 ,15965   ,101,101.1,101.1
XS GIS Cut Line= 3
2278919.75155488633631.0807233372279065.27627018 633879.40848613
2279856.27440984634115.432124575
#Sta/Elev= 30
       0 2190.31     7.7 2187.47      21 2185.98    95.2 2183.16   119.5 2185.56
   238.6 2181.07   311.7 2180.86     372 2182.92   386.9 2178.54   394.5 2174.34
   403.6  2174.1   420.2  2174.9   425.32178.369   428.6 2181.52   441.1 2182.44
   520.4 2181.84   545.5 2184.11   599.7 2181.77   699.7 2183.77   733.3  2187.3
   754.5 2196.24   766.7 2198.32   770.9 2199.94   787.6 2214.53   829.3 2242.93
   908.6 2302.38   918.5 2304.74   928.1 2312.88   944.2 2322.57  1113.3 2420.54
#Mann= 7 ,-1,0
       0     .05       0      60     .06       0     130     .05       0
     280      .1       0  307.83     .05       0   386.9    .045       0
   425.3      .1       0
Bank Sta=386.9,425.3
XS Rating Curve= 0 ,0
Exp/Cntr(USF)=0,0
Exp/Cntr=0.3,0.1

Type RM Length L Ch R = 1 ,15864   ,885.8,888.1,887.1
XS GIS Cut Line= 3
 2278807.3657132633689.0863190442278979.15953723633959.146201821
2279770.15767689634195.169840266
#Sta/Elev= 30
       0 2193.37    53.7 2193.37    68.6  2186.5   120.7 2182.61   371.2 2177.36
   421.3 2180.63   471.4 2180.04   480.1    2176   483.9 2173.46   488.1 2172.17
   500.6 2172.12     509 2172.56   514.12176.198   517.3 2179.48   521.8 2181.03
   609.2 2179.36   709.3 2182.95     797 2182.75   805.3 2183.48   813.7 2185.66
   827.3  2191.7   847.1 2204.02   855.4  2207.4   884.7  2226.8   952.7 2274.15
     964 2283.53   976.5 2287.01   984.8  2294.2  1005.7    2307  1145.5 2386.54
#Mann= 5 ,-1,0
       0     .06       0     150     .05       0  330.07      .1       0
   480.1    .045       0   514.1      .1       0
Bank Sta=480.1,514.1
XS Rating Curve= 0 ,0
Exp/Cntr(USF)=0,0
Exp/Cntr=0.3,0.1

Type RM Length L Ch R = 1 ,14976   ,674.9,677.5,679.5
XS GIS Cut Line= 2
2278333.41923059 634624.575394032279241.91405538 634883.98836182
#Sta/Elev= 30
       0 2173.85   222.8 2173.92   281.6 2166.29   364.1 2165.33   385.6 2165.84
   418.9 2164.82     448 2165.55   477.1 2164.32   538.8 2164.17   576.9 2162.92
     606 2165.03   618.5 2163.43   635.2 2159.78   680.9 2162.08   722.5 2160.27
   730.8 2161.37   740.52159.226   750.2 2157.45   772.4 2157.68   777.5 2159.37
   784.9 2162.74   789.2 2166.22   805.7 2184.35     814 2194.87   822.4 2202.83
   905.4 2255.15     918 2262.21   926.4 2265.32   931.4 2265.13   944.8 2261.42
#Mann= 8 ,-1,0
       0     .05       0     270      .1       0     380     .05       0
     480      .1       0     490     .05       0     580      .1       0
   740.5    .045       0   777.5      .1       0
#XS Ineff= 2 , 0
          719.49 2172.11
Permanent Ineff=
       F       F
Bank Sta=740.5,777.5
XS Rating Curve= 0 ,0
Exp/Cntr(USF)=0,0
Exp/Cntr=0.3,0.1

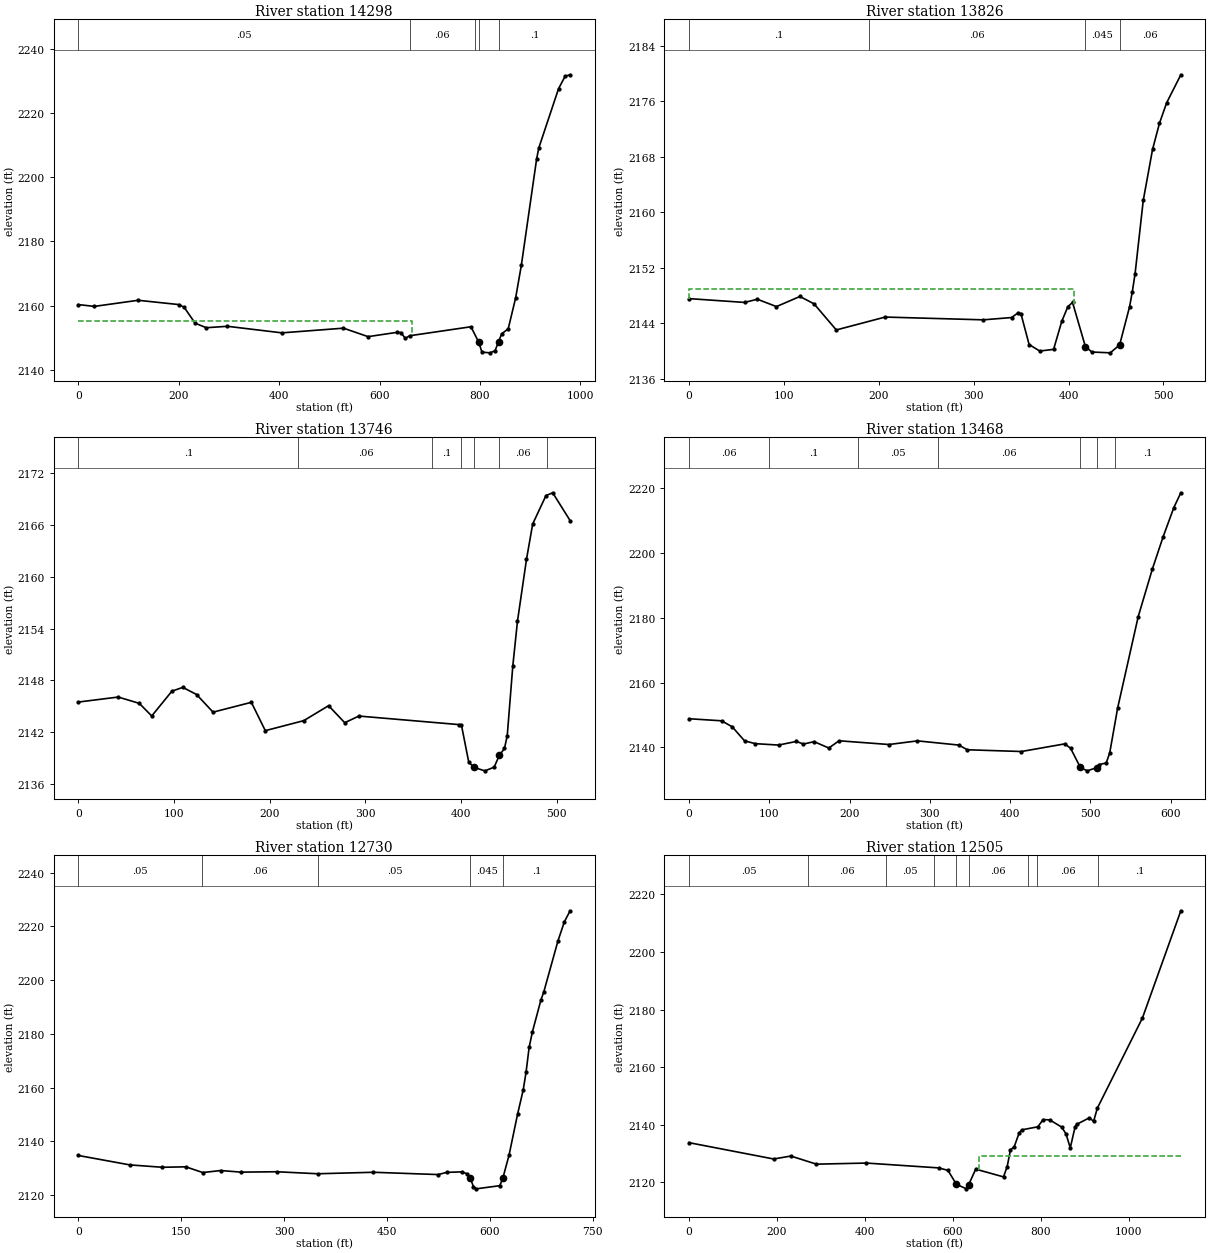
Type RM Length L Ch R = 1 ,14298   ,467.1,472.6,482.1
XS GIS Cut Line= 2
2278090.81600844635131.5945514762278989.30058884635521.990407499
#Sta/Elev= 30
       0 2160.32      32 2159.76   119.2 2161.66   199.9 2160.33   210.8 2159.49
   232.6 2154.54   254.9 2153.12   297.1 2153.56   405.5 2151.52   528.2 2152.98
   577.2 2150.34   633.9 2151.66   642.6  2151.6   651.3  2149.8     660 2150.62
   782.1 2153.42   797.42148.666     804 2145.52   820.1  2145.3   830.1 2145.97
   837.1 2148.76   843.2  2151.2   856.3 2152.78   871.1 2162.39   882.5 2172.59
     913 2205.76   917.3 2209.12   956.6 2227.54   969.7 2231.42   979.6 2231.86
#Mann= 5 ,-1,0
       0     .05       0     660     .06       0     790      .1       0
   797.4    .045       0   837.1      .1       0
#XS Ineff= 2 , 0
          664.26 2155.09
Permanent Ineff=
       F       F
Bank Sta=797.4,837.1
XS Rating Curve= 0 ,0
Exp/Cntr(USF)=0,0
Exp/Cntr=0.3,0.1

Type RM Length L Ch R = 1 ,13826   ,79.9,80.1,80.7
XS GIS Cut Line= 2
2278321.65504613 635490.803546992278627.52035621635909.204207004
#Sta/Elev= 30
       0 2147.53    58.5 2146.98      72 2147.44    92.1 2146.38   116.9 2147.84
   131.8 2146.77   155.2 2143.01   206.7 2144.87   310.1 2144.47   339.9  2144.8
     347  2145.5   349.8 2145.35   358.4 2140.91   369.6 2139.97   384.2 2140.21
   392.8 2144.24   399.3 2146.39   404.2 2146.97   417.7 2140.62   424.5 2139.83
   443.9 2139.71   453.8 2140.85   464.3 2146.37   467.2 2148.54   470.1 2151.14
   478.7 2161.69   488.5 2169.05   495.8 2172.82   503.4 2175.78   518.3 2179.81
#Mann= 4 ,-1,0
       0      .1       0     190     .06       0   417.7    .045       0
   453.8     .06       0
#XS Ineff= 2 , 0
          405.46 2148.93
Permanent Ineff=
       F       F
Bank Sta=417.7,453.8
XS Rating Curve= 0 ,0
Exp/Cntr(USF)=0,0
Exp/Cntr=0.3,0.1

Type RM Length L Ch R = 1 ,13746   ,276.4,277.7,280.4
XS GIS Cut Line= 2
2278268.27289296635536.9718956812278562.59611587635958.258077489
#Sta/Elev= 30
       0  2145.5    41.7 2146.08    63.7 2145.35    76.7 2143.89    97.8 2146.76
   109.2  2147.2   123.6 2146.37   140.8 2144.33   180.8 2145.47   195.4 2142.19
   235.6 2143.35   261.5 2145.08   278.4 2143.11   293.2 2143.88   397.9 2142.89
   400.4  2142.8     408 2138.54   413.62137.931   424.8 2137.54   434.5 2137.96
   439.92139.321   445.3 2140.13   448.2  2141.6     454 2149.66   458.9 2154.86
   468.3    2162   474.8 2166.11   488.7  2169.4   495.7 2169.72   513.9  2166.5
#Mann= 7 ,-1,0
       0      .1       0     230     .06       0     370      .1       0
     400     .06       0   413.6    .045       0   439.9     .06       0
     490      .1       0
Bank Sta=413.6,439.9
XS Rating Curve= 0 ,0
Exp/Cntr(USF)=0,0
Exp/Cntr=0.3,0.1

Type RM Length L Ch R = 1 ,13468   ,724.5,737.6,741.2
XS GIS Cut Line= 2
2278048.49123533635560.644786576 2278313.3062492636113.051733341
#Sta/Elev= 30
       0 2148.83    40.5 2148.19    53.8 2146.34    69.1 2142.02    82.5 2141.14
   111.5 2140.71   133.7 2141.83   142.5 2141.02   155.8 2141.76   174.1  2139.8
   186.9 2142.03     249 2140.88   284.5    2142     336 2140.71   346.6 2139.26
     414 2138.72   467.9 2141.07   475.2 2139.76   487.5 2133.79     496 2132.76
   508.2 2133.77   510.7  2134.7   519.6 2135.17     524 2138.26   533.9 2152.14
   559.5 2180.31   577.3 2195.12   590.6 2204.97   603.9 2213.95   612.6 2218.51
#Mann= 7 ,-1,0
       0     .06       0     100      .1       0     210     .05       0
     310     .06       0   487.5    .045       0   508.2     .06       0
     530      .1       0
Bank Sta=487.5,508.2
XS Rating Curve= 0 ,0
Exp/Cntr(USF)=0,0
Exp/Cntr=0.3,0.1

Type RM Length L Ch R = 1 ,12730   ,211.9,225,231.3
XS GIS Cut Line= 2
2277584.05653535635975.1453411682277839.21722556636644.942152973
#Sta/Elev= 30
       0 2134.77    74.9 2131.27   122.6 2130.38   156.6 2130.55   181.4 2128.42
   207.6 2129.17   237.2 2128.57     289 2128.72   348.9 2127.97   430.2 2128.52
   524.4 2127.67   537.2 2128.49   558.6 2128.67   567.2 2127.92   571.5 2126.25
   575.8 2123.22     580 2122.36   614.3 2123.54   618.7 2126.28   627.8  2134.9
   640.2 2150.09   648.5 2159.23   652.6 2165.74   657.1 2175.02   661.9 2180.81
   674.2 2192.54   678.5 2195.66   699.1 2214.58   708.4 2221.66   716.8 2225.78
#Mann= 5 ,-1,0
       0     .05       0     180     .06       0     350     .05       0
   571.5    .045       0   618.7      .1       0
Bank Sta=571.5,618.7
XS Rating Curve= 0 ,0
Exp/Cntr(USF)=0,0
Exp/Cntr=0.3,0.1

Type RM Length L Ch R = 1 ,12505   ,81.1,80.4,86.6
XS GIS Cut Line= 5
2277508.84509054636014.1610843962277656.03757135636383.389680317
2277551.25648331636700.2277322222277409.05357813636824.967122736
2277458.94933433637017.065784127
#Sta/Elev= 30
       0 2133.77   192.6  2128.1   231.5 2129.13   289.8 2126.31   403.6 2126.69
   567.9 2125.01     589 2124.16   608.2 2119.32   631.1 2117.74   636.2 2119.19
   652.2 2124.58   715.4 2121.89   723.8 2125.48   731.2 2131.28   739.7  2132.3
   750.8 2137.08   756.7 2138.21   793.6 2139.28   805.4 2141.78   820.4 2141.69
   847.9 2139.16   857.7 2136.78   867.3 2131.95   878.2 2139.23   881.5  2140.1
   910.9 2142.41   920.4 2141.16   928.8 2145.73  1031.4 2177.03  1118.8 2214.28
#Mann= 9 ,-1,0
       0     .05       0     270     .06       0  447.49     .05       0
  557.49     .06       0   608.2    .045       0   636.2     .06       0
   771.2      .1       0   791.2     .06       0  930.36      .1       0
#XS Ineff= 2 , 0
                          660.11         2129.12
Permanent Ineff=
       F       F
Bank Sta=608.2,636.2
XS Rating Curve= 0 ,0
Exp/Cntr(USF)=0,0
Exp/Cntr=0.3,0.1

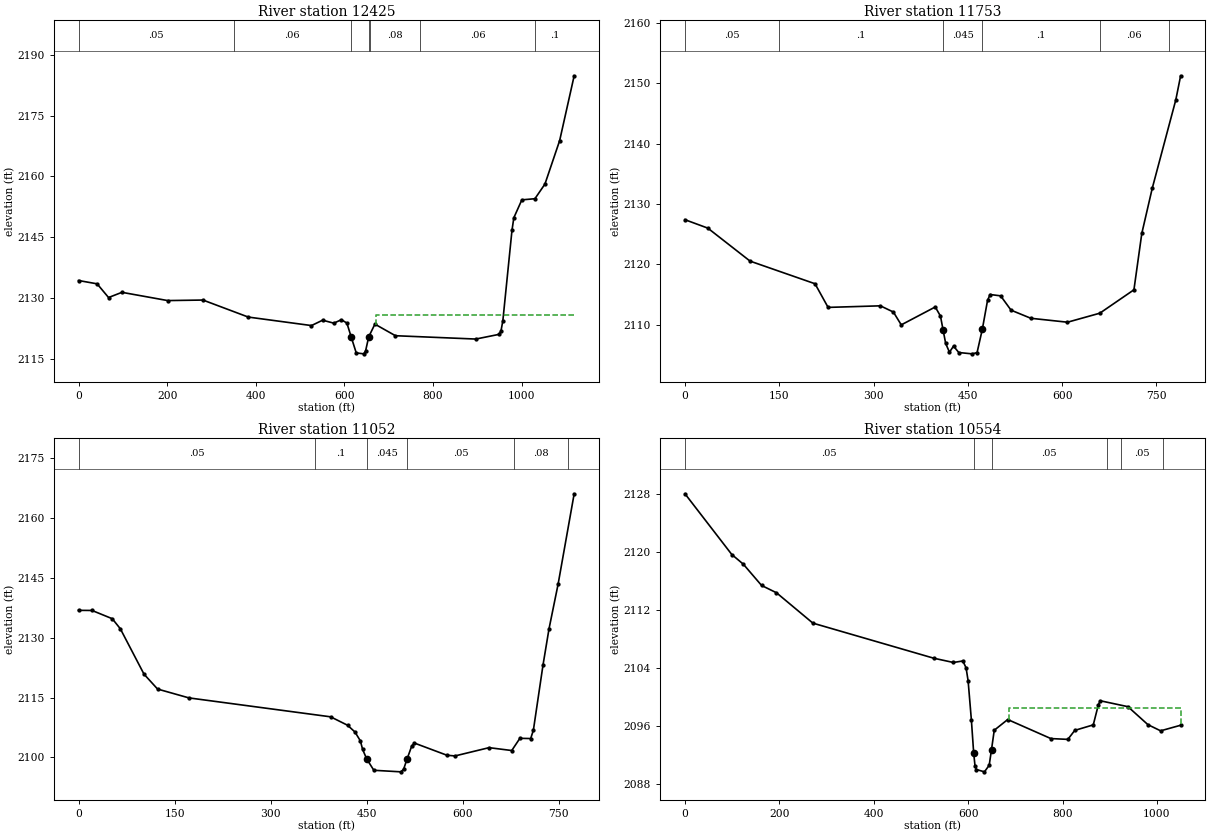
Type RM Length L Ch R = 1 ,12425   ,682.4,672,659.9
XS GIS Cut Line= 5
2277430.25927452636014.1610843962277577.45175532636383.389680317
2277472.67066729636700.2277322222277330.46776211636824.967122736
2277380.36351831637017.065784127
#Sta/Elev= 30
       0 2134.39      42 2133.57    67.8  2130.2      98 2131.48   201.3 2129.45
   280.9 2129.58   383.2 2125.39   525.8  2123.3     551 2124.62   576.3 2123.89
   593.4 2124.74   605.8 2123.91   615.2  2120.6   626.9 2116.57   643.7 2116.34
   647.9 2117.01   655.12120.539     669 2123.65   715.4  2120.8   896.8 2119.98
   949.5 2121.14   953.6 2121.96   957.8 2124.46   978.4 2146.71   982.6 2149.83
  1000.7 2154.24  1030.2 2154.52  1052.8 2158.12    1086 2168.81  1118.8 2184.78
#Mann= 7 ,-1,0
       0     .05       0     350     .06       0   615.2    .045       0
   655.1      .1       0  657.49     .08       0   771.2     .06       0
 1030.36      .1       0
#XS Ineff= 2 , 0
                          671.04            2126
Permanent Ineff=
       F       F
Bank Sta=615.2,655.1
XS Rating Curve= 0 ,0
Exp/Cntr(USF)=0,0
Exp/Cntr=0.3,0.1

Type RM Length L Ch R = 1 ,11753   ,692.6,701,686.3
XS GIS Cut Line= 2
2276815.03056624636386.2375642872277031.20837323637144.631837971
#Sta/Elev= 30
       0  2127.4    36.3 2126.01   103.6 2120.55   206.9 2116.81   227.7  2112.9
   310.9 2113.16   331.6 2112.13   344.1 2110.01   398.2 2112.97   406.5 2111.46
   410.7 2109.14   414.8 2106.93   420.8 2105.49   427.3  2106.5   435.6 2105.44
   456.4 2105.22   464.7 2105.41   473.1 2109.29   481.4 2114.07   485.5 2115.03
   502.2 2114.81   518.8 2112.44   550.3  2111.1   608.6 2110.45     660 2111.94
   714.3 2115.81   726.8 2125.12   743.4 2132.58   780.9 2147.21   788.6  2151.2
#Mann= 6 ,-1,0
       0     .05       0     150      .1       0   410.7    .045       0
   473.1      .1       0     660     .06       0     770      .1       0
Bank Sta=410.7,473.1
XS Rating Curve= 0 ,0
Exp/Cntr(USF)=0,0
Exp/Cntr=0.3,0.1

Type RM Length L Ch R = 1 ,11052   ,504.8,498.4,488.7
XS GIS Cut Line= 3
2276266.29201379636772.2604245992276495.93663498637449.712057111
2276536.12444369637492.770423584
#Sta/Elev= 30
       0 2136.88    21.1 2136.85    52.7 2134.78    65.3 2132.26   102.3 2120.86
   123.5 2117.12   172.5  2114.9   393.8 2110.15   420.2 2108.04   431.8 2106.34
   440.2 2104.13   443.8 2101.95   450.1 2099.59   461.3 2096.73   503.6 2096.34
   507.8    2097   513.2 2099.56   520.5 2102.83   524.7 2103.56   575.4 2100.51
     588 2100.33   641.3 2102.41   676.7 2101.69   689.4 2104.75   706.3  2104.7
   710.5  2106.8   725.5 2123.12   734.9 2132.23   749.1 2143.44   774.2 2166.14
#Mann= 6 ,-1,0
       0     .05       0     370      .1       0   450.1    .045       0
   513.2     .05       0     680     .08       0  765.32      .1       0
Bank Sta=450.1,513.2
XS Rating Curve= 0 ,0
Exp/Cntr(USF)=0,0
Exp/Cntr=0.3,0.1

Type RM Length L Ch R = 1 ,10554   ,720.1,722.6,722.5
XS GIS Cut Line= 3
 2275798.5228044636805.538854519 2275871.3364925637273.626849411
2276204.19906664637744.315333164
#Sta/Elev= 30
       0 2128.03    99.2 2119.65   123.7 2118.31   162.3 2115.38   193.9 2114.37
     271 2110.18   527.1 2105.34   568.7 2104.75   588.8 2104.96   595.6 2104.01
   599.9 2102.23   606.8 2096.84   611.7 2092.27   614.6 2090.44   617.5 2089.98
   634.5 2089.66   644.6 2090.57   649.5 2092.74   655.3  2095.4   683.8 2096.88
   775.3 2094.25   811.2 2094.14   825.9 2095.38   865.1 2096.14   875.8 2098.89
   879.8 2099.47   938.6 2098.65   980.9 2096.17  1007.8 2095.32  1050.2 2096.09
#Mann= 6 ,-1,0
       0     .05       0   611.7    .045       0   649.5     .05       0
  893.72     .06       0  923.72     .05       0 1013.72     .06       0
#XS Ineff= 2 , 0
                          686.34         2098.53
Permanent Ineff=
       F       F
Bank Sta=611.7,649.5
XS Rating Curve= 0 ,0
Exp/Cntr(USF)=0,0
Exp/Cntr=0.3,0.1