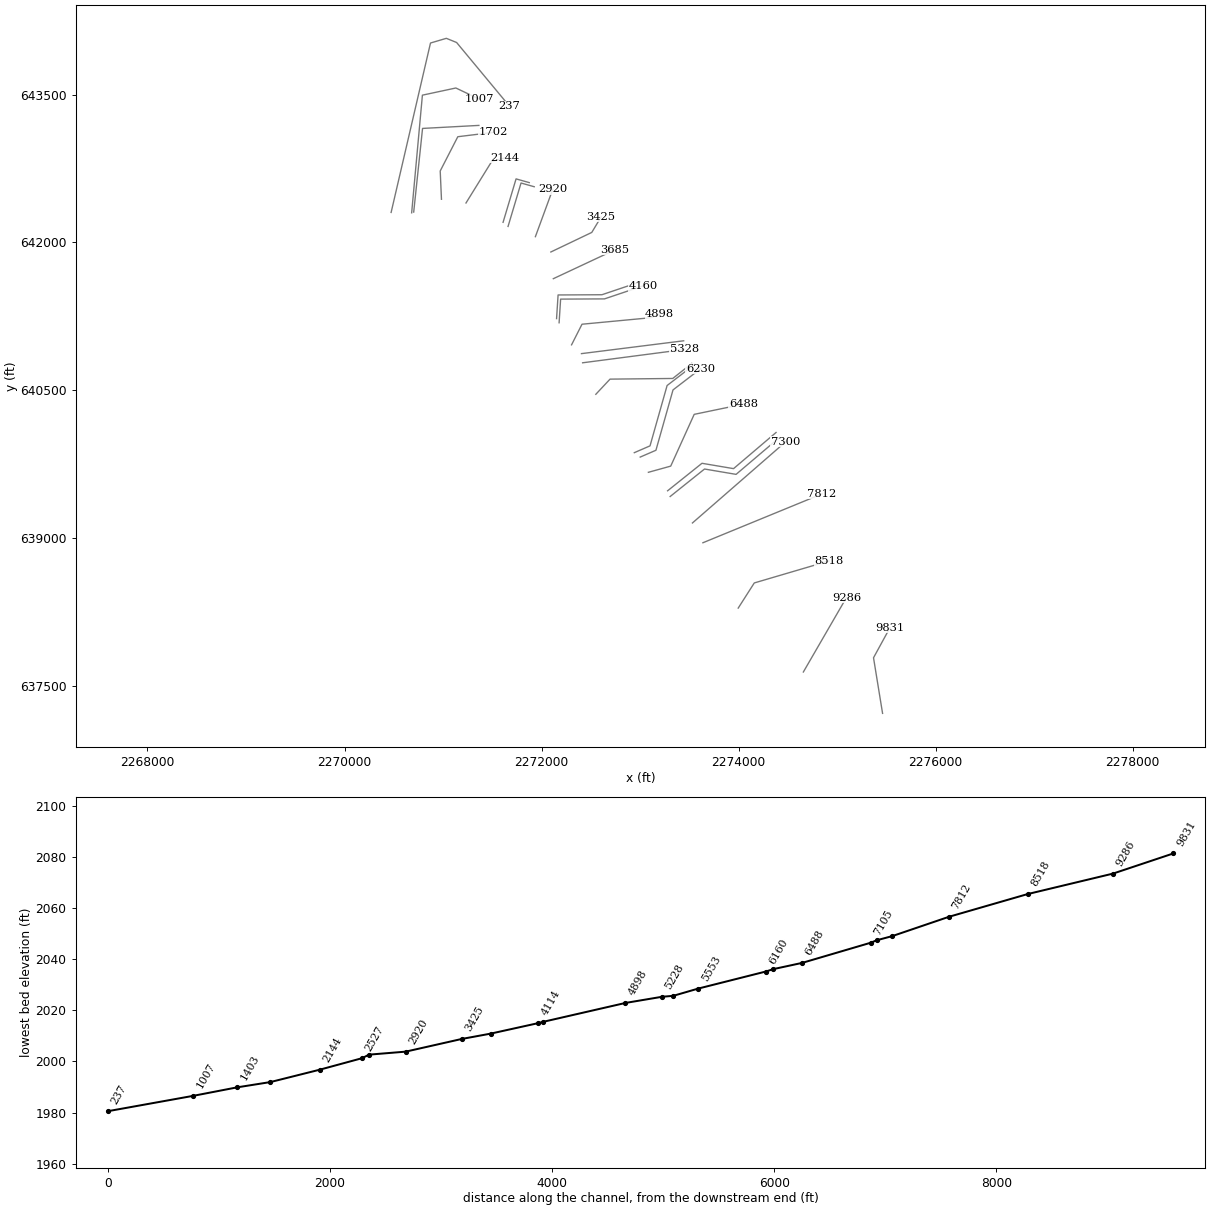
HEC-RAS study SHAVRRN.prj: SHAVRRN

--- SHAVRRN.g01 (geometry) --- (continued)

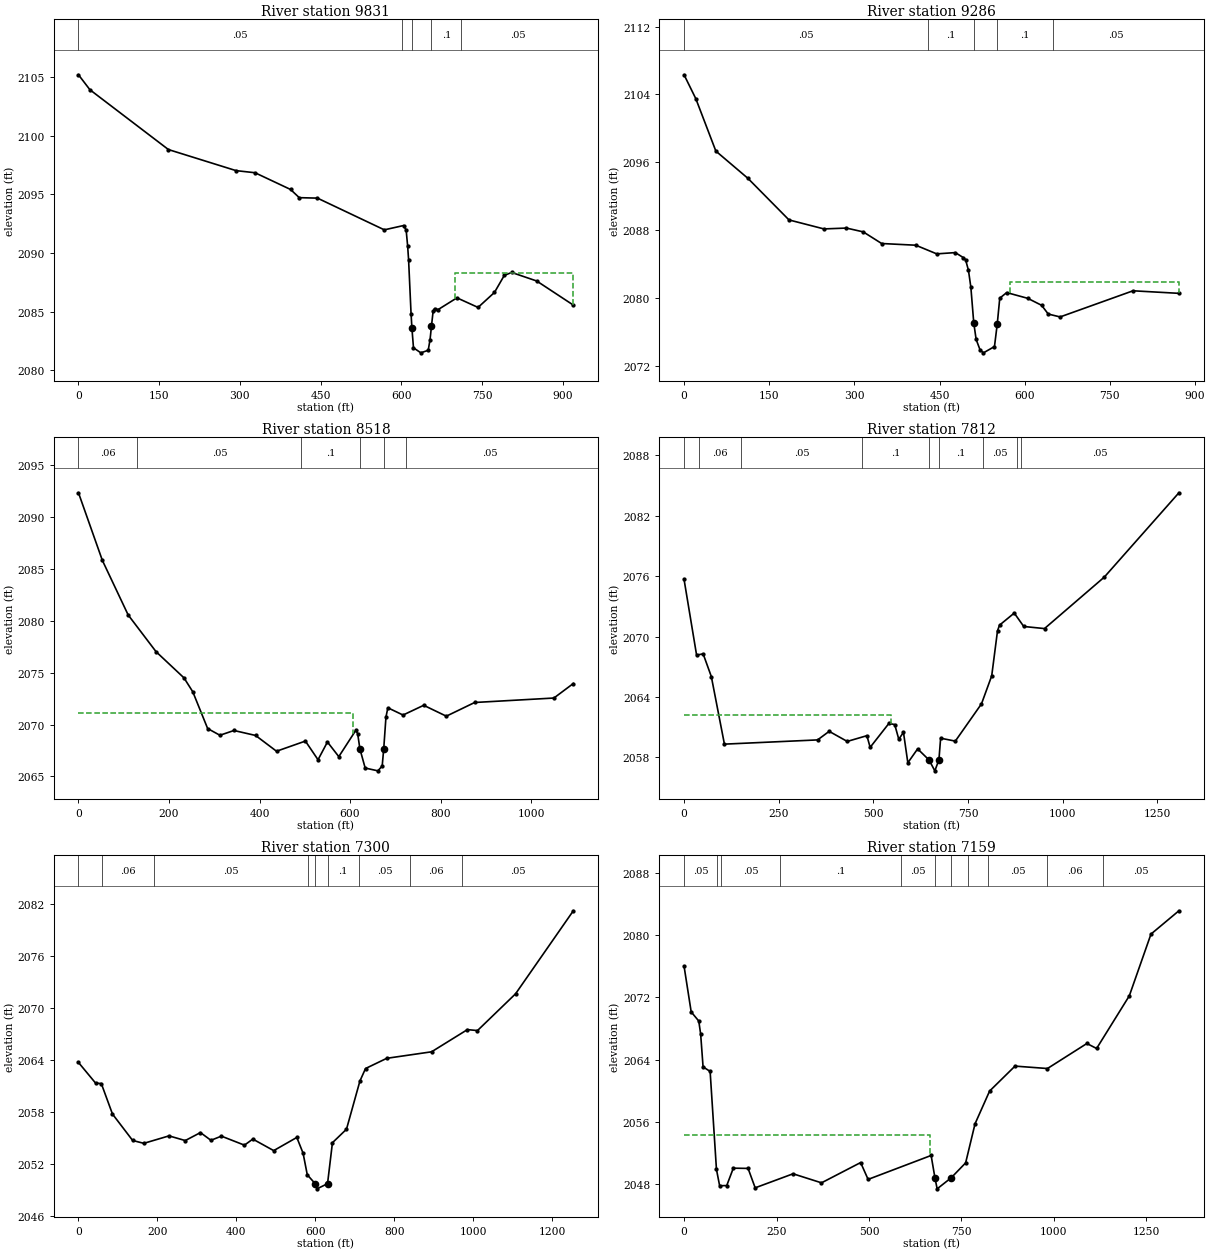
Type RM Length L Ch R = 1 ,9831    ,544.7,544.4,543.6
XS GIS Cut Line= 3
2275460.89689596 637220.10943768 2275369.0180466637784.508083725
 2275535.9131036638089.803649564
#Sta/Elev= 30
       0 2105.23    21.3 2103.95   167.2 2098.84   292.9 2097.04   328.1 2096.86
   394.2 2095.43   410.4 2094.73   444.2 2094.69   568.5 2091.98   604.5 2092.35
   609.1 2091.95   611.8 2090.62   613.6 2089.43   618.2 2084.81   619.82083.572
   622.7  2081.9   636.4 2081.47   650.1 2081.69   653.5  2082.6   656.1 2083.74
   659.2 2085.03   661.8 2085.25   668.3 2085.16   703.5 2086.17   742.7 2085.35
   773.2 2086.63   791.4 2088.08   805.1 2088.34   851.7 2087.61   919.8 2085.55
#Mann= 5 ,-1,0
       0     .05       0  601.83      .1       0   619.8    .045       0
   656.1      .1       0  711.83     .05       0
#XS Ineff= 2 , 0
                          700.36          2088.3
Permanent Ineff=
       F       F
Bank Sta=619.8,656.1
XS Rating Curve= 0 ,0
Exp/Cntr(USF)=0,0
Exp/Cntr=0.3,0.1

Type RM Length L Ch R = 1 ,9286    ,788.3,768.7,754.9
XS GIS Cut Line= 2
2274656.87544205637640.0116702022275093.49499924638394.263420309
#Sta/Elev= 30
       0 2106.32    20.8 2103.49      56 2097.33   112.3 2094.13   184.8 2089.22
   246.3 2088.16     286 2088.26   315.6 2087.81     348 2086.44   408.1 2086.24
     445 2085.22   477.7 2085.37   492.1 2084.77   495.9 2084.51   500.9 2083.27
   505.1 2081.29510.19992077.094   514.4 2075.14   521.4 2073.89   527.3 2073.56
   546.7  2074.3   551.62076.971     556    2080   568.2 2080.66   605.4 2079.98
   629.7 2079.16   641.4 2078.13   662.3 2077.79   790.7 2080.87   871.5 2080.57
#Mann= 5 ,-1,0
       0     .05       0     430      .1       0510.1999    .045       0
   551.6      .1       0     650     .05       0
#XS Ineff= 2 , 0
                          573.29         2081.89
Permanent Ineff=
       F       F
Bank Sta=510.1999,551.6
XS Rating Curve= 0 ,0
Exp/Cntr(USF)=0,0
Exp/Cntr=0.3,0.1

Type RM Length L Ch R = 1 ,8518    ,695,706,705
XS GIS Cut Line= 3
2273995.87143612638288.6815968762274158.89076598638543.842287087
2274917.28503967638767.107891022
#Sta/Elev= 30
       0 2092.35    52.8 2085.83   109.8 2080.57   171.4 2077.03   233.2  2074.5
   252.6 2073.16   285.4 2069.62   312.5 2068.97   343.6 2069.43   391.4 2068.95
   437.6 2067.43   501.4 2068.41   529.3 2066.61   550.1 2068.32   575.2 2066.91
   612.7 2069.44   616.9 2069.13   621.8 2067.66   633.5 2065.81   661.6 2065.54
   671.1 2066.01   674.52067.679   679.4 2070.72   683.6 2071.62   717.2 2070.92
   762.8 2071.86   812.8 2070.81   875.4 2072.13  1050.5 2072.56  1093.4 2073.96
#Mann= 6 ,-1,0
       0     .06       0     130     .05       0  492.79      .1       0
   621.8    .045       0   674.5      .1       0  722.79     .05       0
#XS Ineff= 2 , 0
          607.36 2071.08
Permanent Ineff=
       F       F
Bank Sta=621.8,674.5
XS Rating Curve= 0 ,0
Exp/Cntr(USF)=0,0
Exp/Cntr=0.3,0.1

Type RM Length L Ch R = 1 ,7812    ,505.8,511.8,513.9
XS GIS Cut Line= 2
2273637.54392364638951.7843782282274846.40707016639447.930164751
#Sta/Elev= 30
       0 2075.67    33.1 2068.16    50.4 2068.28      72 2066.03   106.6 2059.32
   352.6 2059.74   383.2 2060.59   430.9 2059.59   482.8 2060.16   491.4    2059
     541 2061.38   556.3 2061.26     567 2059.81   579.4 2060.49   590.9 2057.47
   616.8 2058.85   647.1 2057.74   662.2 2056.67     673 2057.76   677.5 2059.91
   716.3 2059.62   785.4 2063.32   812.4  2066.1   827.7 2070.57     833 2071.13
   871.9 2072.33     897    2071   951.8 2070.79  1109.7  2075.9  1306.7 2084.27
#Mann= 9 ,-1,0
       0     .05       0      40     .06       0     150     .05       0
     470      .1       0   647.1    .045       0     673      .1       0
     790     .05       0     880     .06       0     890     .05       0
#XS Ineff= 2 , 0
          546.86 2062.23
Permanent Ineff=
       F       F
Bank Sta=647.1,673
XS Rating Curve= 0 ,0
Exp/Cntr(USF)=0,0
Exp/Cntr=0.3,0.1

Type RM Length L Ch R = 1 ,7300    ,154.9,140.9,119.9
XS GIS Cut Line= 2
2273531.22696938 639152.605291822274476.26656276639975.577271052
#Sta/Elev= 30
       0 2063.67    43.5 2061.28    57.8 2061.24    86.1 2057.72   137.2 2054.67
   165.5 2054.34   229.3  2055.2   270.4 2054.66   308.9 2055.58   335.4 2054.69
   361.9 2055.17   420.3 2054.13   441.5 2054.83   494.4  2053.5   552.9 2055.02
   568.8  2053.2   579.4 2050.71   599.3 2049.69   603.9 2049.09   630.72049.684
   643.1 2054.41   678.7 2055.97   712.7 2061.53   726.9 2062.97   780.7 2064.15
   894.2  2064.9   984.9 2067.46  1010.4 2067.35  1106.8 2071.59  1253.1 2081.17
#Mann= 9 ,-1,0
       0     .05       0      60     .06       0     190     .05       0
     580      .1       0   599.3    .045       0   630.7      .1       0
     710     .05       0     840     .06       0     970     .05       0
Bank Sta=599.3,630.7
XS Rating Curve= 0 ,0
Exp/Cntr(USF)=0,0
Exp/Cntr=0.3,0.1

Type RM Length L Ch R = 1 ,7159    ,53.8,54,59.6
XS GIS Cut Line= 4
 2273305.1270342639421.0662330092273653.89980263639700.084447756
2273974.25404919   639645.8309062274405.69888125640012.688188351
#Sta/Elev= 30
       0    2076    19.3 2070.13    39.8 2068.96    44.9 2067.28    51.4 2063.08
    70.5  2062.5    87.6 2049.93    96.2 2047.84   115.4 2047.86   133.2 2050.09
   173.1 2050.06   192.3 2047.57   294.7 2049.37   371.6 2048.21   477.4 2050.81
   497.6 2048.65     668 2051.72   678.42048.825   684.3 2047.44   722.3 2048.86
   761.3 2050.77   786.7 2055.78   826.1 2059.98   894.8 2063.18   982.5 2062.87
  1089.1 2066.08  1115.4 2065.44  1203.8 2072.19  1262.4 2080.11  1337.9  2083.1
#Mann= 11 ,-1,0
       0     .05       0      90     .06       0     100     .05       0
     260      .1       0  586.65     .05       0   678.4    .045       0
   722.3     .05       0  766.65      .1       0  821.56     .05       0
  981.56     .06       0 1131.56     .05       0
#XS Ineff= 2 , 0
          666.14 2054.29
Permanent Ineff=
       F       F
Bank Sta=678.4,722.3
XS Rating Curve= 0 ,0
Exp/Cntr(USF)=0,0
Exp/Cntr=0.3,0.1

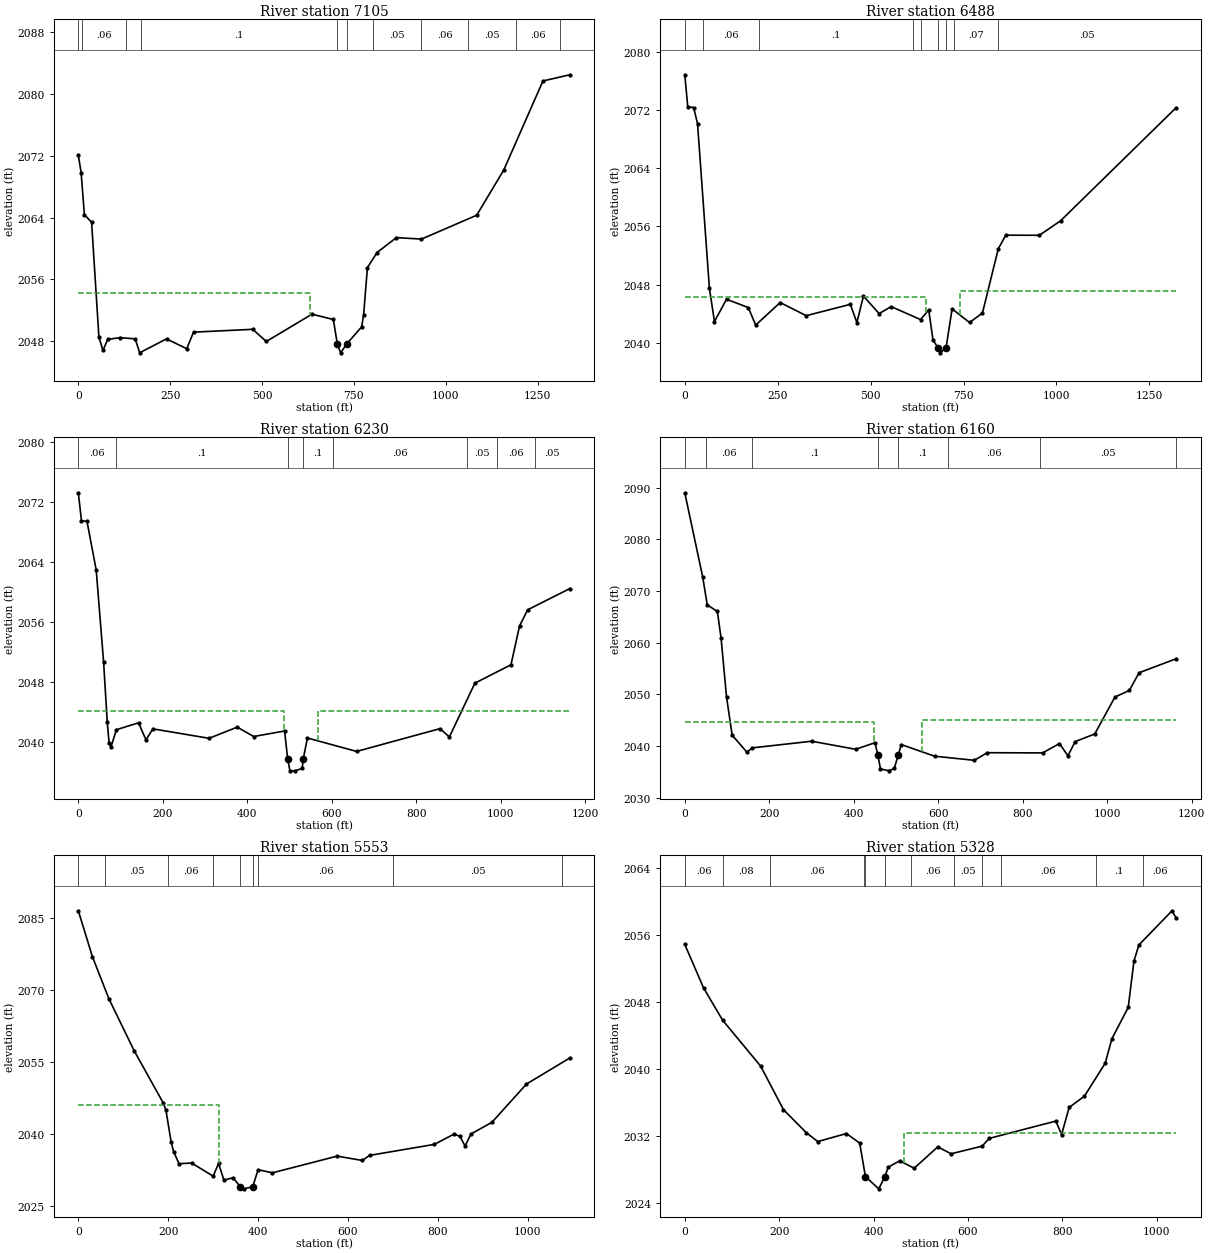
Type RM Length L Ch R = 1 ,7105    ,594.8,617,627
XS GIS Cut Line= 4
2273279.29201431639479.1950277482273628.06478275639758.213242495
2273948.41902931639703.9597007382274379.86386137 640070.81698309
#Sta/Elev= 30
       0 2072.12     7.7 2069.83    16.5  2064.4    36.2 2063.39    56.1 2048.51
    67.2 2046.79      80 2048.22   113.8 2048.45   154.8 2048.29   167.1 2046.49
   240.1 2048.29   295.2 2047.01   313.6 2049.16   474.8 2049.53   511.7 2047.95
     636 2051.49   694.2  2050.8   705.12047.604   714.1 2046.48   730.7 2047.64
   771.3 2049.85   776.5 2051.34     787 2057.53   813.2 2059.48   865.8 2061.41
   934.1 2061.22  1084.4 2064.31  1158.2 2070.18  1264.8 2081.71  1337.9 2082.51
#Mann= 11 ,-1,0
       0     .05       0      10     .06       0     130     .05       0
     170      .1       0   705.1    .045       0   730.7      .1       0
  801.56     .05       0  931.56     .06       0 1061.56     .05       0
 1191.56     .06       0 1311.56     .05       0
#XS Ineff= 2 , 0
          629.75 2054.23
Permanent Ineff=
       F       F
Bank Sta=705.1,730.7
XS Rating Curve= 0 ,0
Exp/Cntr(USF)=0,0
Exp/Cntr=0.3,0.1

Type RM Length L Ch R = 1 ,6488    ,256.6,257.5,259.7
XS GIS Cut Line= 4
 2273084.3524365639666.8146832612273310.86814973639729.593781579
2273549.12444421640254.9058525522274048.91725666640358.532987864
#Sta/Elev= 30
       0 2076.89     8.1 2072.46    23.8 2072.38    34.3 2070.17    66.2  2047.5
    79.8  2042.9   112.3 2045.97   170.8 2044.83   190.8 2042.41   256.6 2045.52
   326.8 2043.71   445.4 2045.27     463 2042.75   480.6 2046.41   522.8    2044
   555.2 2044.96   634.3 2043.17   656.2 2044.49   667.8 2040.37   681.5 2039.27
     687 2038.59   702.92039.279   719.2 2044.64   766.1 2042.77   800.8 2044.07
   843.4 2052.92   863.7  2054.8   953.9 2054.78  1011.1 2056.78  1322.3 2072.38
#Mann= 9 ,-1,0
       0      .1       0      50     .06       0     200      .1       0
  615.05     .05       0  635.05      .1       0   681.5    .045       0
   702.9      .1       0  725.05     .07       0  841.87     .05       0
#XS Ineff= 2 , 0
          649.96 2046.35  739.93         2047.16
Permanent Ineff=
       F       F
Bank Sta=681.5,702.9
XS Rating Curve= 0 ,0
Exp/Cntr(USF)=0,0
Exp/Cntr=0.3,0.1

Type RM Length L Ch R = 1 ,6230    ,70.9,70.1,69.9
XS GIS Cut Line= 4
2273001.28386273639821.3722304272273160.74954697639890.455044891
2273334.10626212640502.8778942592273614.28937791640718.021864195
#Sta/Elev= 30
       0 2073.27     7.5 2069.55    20.6 2069.45    42.4 2062.96    59.8 2050.75
    68.5  2042.7    72.9 2039.87    77.3 2039.35    90.3 2041.66   142.6 2042.58
   160.1 2040.31   176.6 2041.77   309.6 2040.51   376.2    2042   415.3 2040.75
   488.4 2041.49   495.52037.785   500.9 2036.19   512.5 2036.17     530 2036.49
   532.3 2037.73   542.4 2040.55   658.8 2038.76   856.2  2041.8   878.4 2040.69
   938.8 2047.87  1024.2 2050.32  1044.5  2055.5  1063.6 2057.65  1163.5 2060.49
#Mann= 8 ,-1,0
       0     .06       0      90      .1       0   495.5    .045       0
   532.3      .1       0  603.79     .06       0  920.27     .05       0
  990.27     .06       0 1080.27     .05       0
#XS Ineff= 2 , 0
          487.43 2044.17  567.51         2044.17
Permanent Ineff=
       F       F
Bank Sta=495.5,532.3
XS Rating Curve= 0 ,0
Exp/Cntr(USF)=0,0
Exp/Cntr=0.3,0.1

Type RM Length L Ch R = 1 ,6160    ,633.3,606.8,586.1
XS GIS Cut Line= 4
2272941.32409707639866.0483714932273100.78978132639935.131185957
2273274.14649646640547.5540353252273554.32961225640762.698005261
#Sta/Elev= 30
       0 2089.02    42.3 2072.77    53.2 2067.32    77.2 2066.05    85.9 2060.89
    98.8 2049.53   112.1 2042.11     147 2038.82     160 2039.65   300.6 2040.93
   404.6 2039.37   450.3 2040.65   456.8 2038.32   463.3 2035.57   483.5  2035.2
     496 2035.68   505.4  2038.3   512.6 2040.28   591.6 2038.03   685.5 2037.24
     716 2038.71   847.1 2038.67     887 2040.49     907  2038.1   924.1 2040.86
   970.6 2042.34  1018.3 2049.49  1052.5 2050.76  1075.3 2054.18  1163.5 2056.91
#Mann= 8 ,-1,0
       0      .1       0      50     .06       0     160      .1       0
   456.8    .045       0   505.4      .1       0  623.79     .06       0
  840.27     .05       0 1163.53     .06       0
#XS Ineff= 2 , 0
          448.09 2044.56  560.58            2045
Permanent Ineff=
       F       F
Bank Sta=456.8,505.4
XS Rating Curve= 0 ,0
Exp/Cntr(USF)=0,0
Exp/Cntr=0.3,0.1

Type RM Length L Ch R = 1 ,5553    ,221.2,225.7,223.7
XS GIS Cut Line= 4
2272550.76850478640458.5414783642272694.91478907640612.353895174
2273331.47273405640619.1514146642273524.76182931640772.020315031
#Sta/Elev= 30
       0 2086.48    31.3 2076.94    67.9 2068.18   124.2 2057.33   189.2 2046.41
   195.1  2044.9   206.4  2038.4   212.1 2036.31   224.1 2033.78   252.1 2033.92
   300.1 2031.19   312.1 2033.83   324.1 2030.35   344.1 2030.85   360.8 2028.97
   368.1 2028.54   388.1 2028.97   400.1 2032.52   432.1 2031.88   576.1 2035.36
   632.1 2034.45   648.2 2035.51   792.1  2037.8   836.1 2039.94   849.3 2039.48
   860.7 2037.46   873.8 2039.97   920.5  2042.4   997.4 2050.38  1093.8 2055.81
#Mann= 9 ,-1,0
       0      .1       0      60     .05       0     200     .06       0
   300.8      .1       0   360.8    .045       0   388.1      .1       0
   400.8     .06       0   700.8     .05       0 1077.39     .06       0
#XS Ineff= 2 , 0
          312.57 2045.95
Permanent Ineff=
       F       F
Bank Sta=360.8,388.1
XS Rating Curve= 0 ,0
Exp/Cntr(USF)=0,0
Exp/Cntr=0.3,0.1

Type RM Length L Ch R = 1 ,5328    ,96.2,99.5,94.1
XS GIS Cut Line= 2
2272416.80038173640778.2380998352273449.16777629640913.096903629
#Sta/Elev= 30
       0 2054.91    39.7 2049.72      80 2045.86   160.7 2040.36   209.1 2035.15
   257.5  2032.4   281.7 2031.34   342.3  2032.3   370.5 2031.16   382.6 2027.16
   410.8 2025.69   423.1 2027.05     431 2028.28   455.2 2029.04   485.9 2028.15
   535.9 2030.71   564.1 2029.88     630  2030.8   644.8 2031.72     786 2033.79
   798.1 2032.18   814.2 2035.42   846.5 2036.77   890.5  2040.7   904.7 2043.63
   939.3 2047.38   951.4  2052.9   961.8 2054.84  1032.1 2058.93  1041.1 2058.03
#Mann= 12 ,-1,0
       0     .06       0      80     .08       0     180     .06       0
     380     .07       0   382.6    .045       0   423.1     .07       0
     480     .06       0     570     .05       0     630     .07       0
     670     .06       0     870      .1       0     970     .06       0
#XS Ineff= 2 , 0
                          463.54         2032.35
Permanent Ineff=
       F       F
Bank Sta=382.6,423.1
XS Rating Curve= 0 ,0
Exp/Cntr(USF)=0,0
Exp/Cntr=0.3,0.1

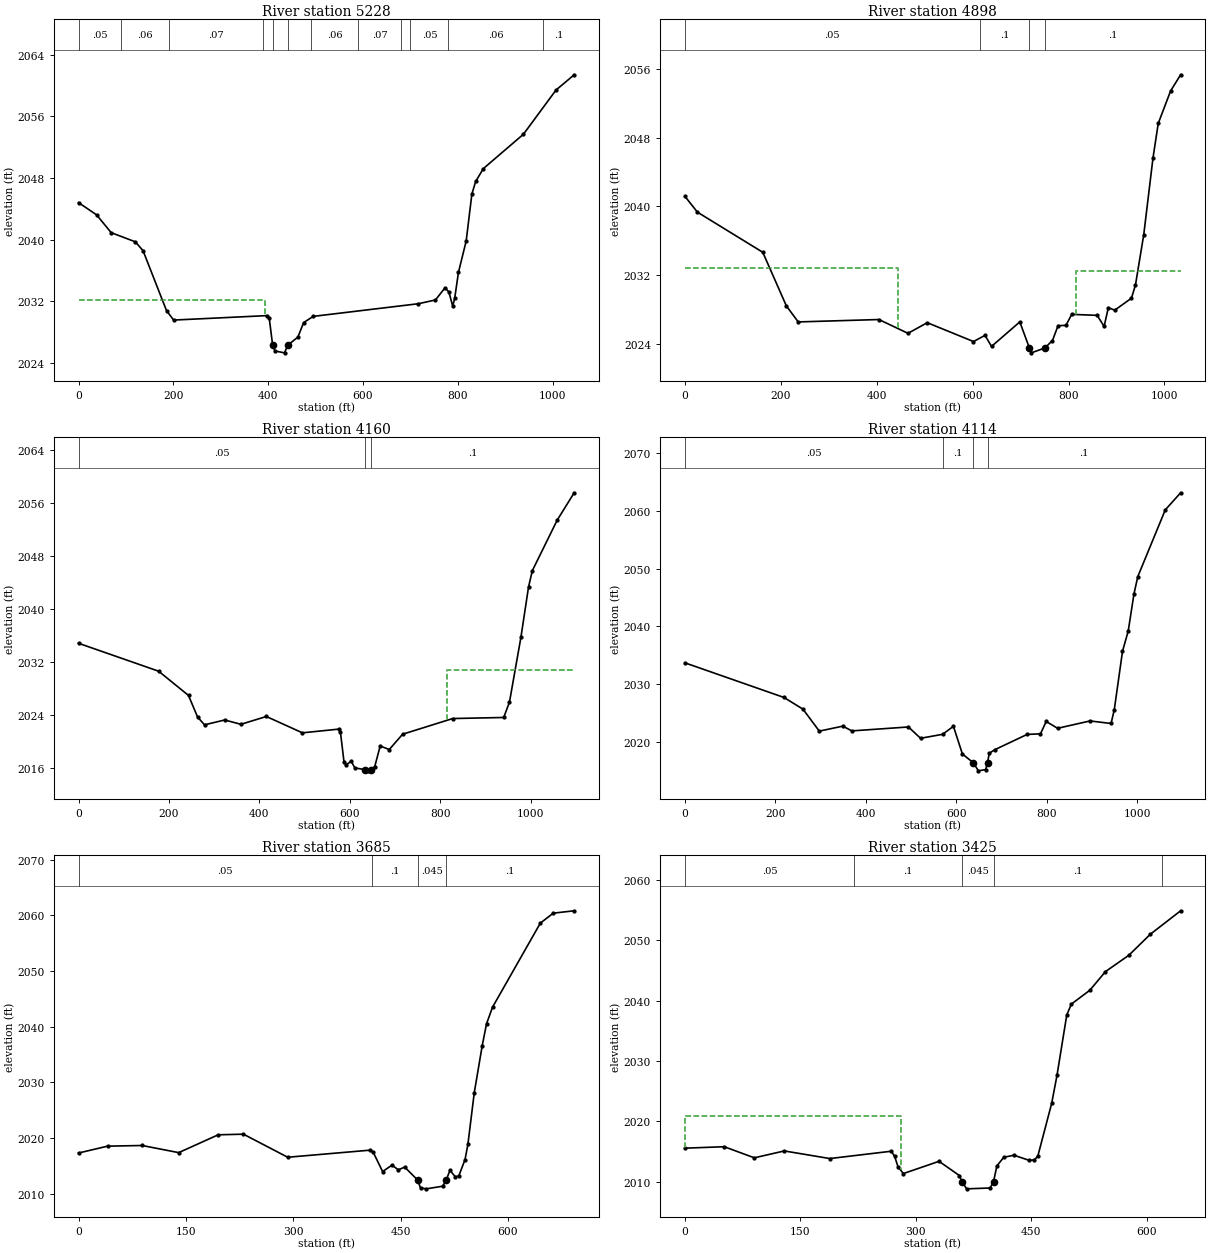
Type RM Length L Ch R = 1 ,5228    ,326.5,330.1,326.4
XS GIS Cut Line= 2
2272405.17462278640871.2441714172273442.19232092641001.452671632
#Sta/Elev= 30
       0 2044.82    38.1 2043.23    68.9 2040.92   119.9 2039.73   136.1 2038.58
   185.6  2030.8   200.6 2029.58   397.7 2030.16   402.1 2029.88   409.22026.401
   414.2 2025.57   434.4 2025.33   441.4 2026.33   462.6 2027.37   474.7 2029.25
   494.9 2030.06   716.6  2031.7   752.7 2032.19     773 2033.78   781.1  2033.2
   789.1 2031.39   793.2 2032.38   801.2 2035.77   817.5 2039.84   829.5 2045.93
   837.5 2047.56   853.7 2049.23   938.3 2053.69  1006.8 2059.41  1045.2  2061.4
#Mann= 12 ,-1,0
       0     .05       0      90     .06       0     190     .07       0
     390     .05       0   409.2    .045       0   441.4     .05       0
     490     .06       0     590     .07       0     680     .06       0
     700     .05       0     780     .06       0     980      .1       0
#XS Ineff= 2 , 0
          393.36 2032.22
Permanent Ineff=
       F       F
Bank Sta=409.2,441.4
XS Rating Curve= 0 ,0
Exp/Cntr(USF)=0,0
Exp/Cntr=0.3,0.1

Type RM Length L Ch R = 1 ,4898    ,676.6,738.5,703.5
XS GIS Cut Line= 4
2272304.44487463640960.4557717072272410.49563401  641169.6063251
2273107.29295817641235.5179517812273199.36896903641273.185410772
#Sta/Elev= 30
       0 2041.18    25.9 2039.34   162.3 2034.65   211.5 2028.39   236.2 2026.52
   404.5  2026.8   465.2 2025.19   505.4 2026.43   601.8 2024.23   625.9 2024.95
   639.4 2023.66   698.4 2026.52   718.62023.457   722.3 2022.91   750.4 2023.47
   766.5 2024.34   778.2 2026.08   794.7 2026.12   806.7  2027.4   859.7 2027.29
   874.3    2026   883.1 2028.19   896.4 2027.89   931.3 2029.29   939.7 2030.84
     957 2036.72   976.2 2045.65   987.2  2049.7    1013  2053.5  1033.9 2055.38
#Mann= 4 ,-1,0
       0     .05       0   614.5      .1       0   718.6    .045       0
   750.4      .1       0
#XS Ineff= 2 , 0
          443.72  2032.8   815.3         2032.48
Permanent Ineff=
       F       F
Bank Sta=718.6,750.4
XS Rating Curve= 0 ,0
Exp/Cntr(USF)=0,0
Exp/Cntr=0.3,0.1

Type RM Length L Ch R = 1 ,4160    ,49.5,45.5,42.9
XS GIS Cut Line= 4
2272177.98024368641184.3362455592272193.43766618 641424.40371549
2272638.56490158641426.7549789672273027.77276697641557.783989813
#Sta/Elev= 30
       0 2034.81   177.2 2030.59   243.3 2026.93   263.3 2023.68   278.7 2022.49
   323.3 2023.22   359.3 2022.57   415.5 2023.75   495.3 2021.28   575.3 2021.84
   579.3 2021.43   587.3 2016.88   591.3 2016.43   603.3 2016.98   611.3 2015.98
     634 2015.72   639.3 2015.54   645.9 2015.72   655.3 2016.19   667.3 2019.29
   687.4 2018.76   716.9 2021.07   827.8 2023.44   940.6  2023.6   953.3 2025.93
   978.6  2035.7   995.5 2043.33  1003.9 2045.78  1058.8  2053.4  1096.4 2057.54
#Mann= 3 ,-1,0
       0     .05       0     634    .045       0   645.9      .1       0
#XS Ineff= 2 , 0
                           815.3          2030.8
Permanent Ineff=
       F       F
Bank Sta=634,645.9
XS Rating Curve= 0 ,0
Exp/Cntr(USF)=0,0
Exp/Cntr=0.3,0.1

Type RM Length L Ch R = 1 ,4114    ,413.7,428.7,433
XS GIS Cut Line= 4
2272152.20720646641226.5608939142272167.66462896641466.628363846
2272612.79186436641468.9796273232273001.99972975641600.008638169
#Sta/Elev= 30
       0  2033.7   219.1 2027.71   261.1 2025.68   297.1 2021.89   349.1 2022.75
   369.1 2021.93   494.3 2022.61   521.1 2020.65   569.9 2021.34   593.8 2022.72
   613.7 2017.93   637.5 2016.44   649.1 2015.02   665.1 2015.24   669.22016.412
   673.1 2018.05   685.1 2018.67   756.8 2021.32   786.4 2021.42     799 2023.56
   824.2 2022.38   896.1 2023.65   942.5 2023.21   949.6 2025.58   967.8 2035.68
   980.5 2039.22   993.2 2045.63  1001.6 2048.61  1062.4 2060.16  1096.4 2063.12
#Mann= 4 ,-1,0
       0     .05       0  570.56      .1       0   637.5    .045       0
   669.2      .1       0
Bank Sta=637.5,669.2
XS Rating Curve= 0 ,0
Exp/Cntr(USF)=0,0
Exp/Cntr=0.3,0.1

Type RM Length L Ch R = 1 ,3685    ,259.9,260.6,260.2
XS GIS Cut Line= 2
2272119.44384137641631.7560281882272746.60703356641925.562208317
#Sta/Elev= 30
       0 2017.33    40.6 2018.56    88.9 2018.68     140  2017.4   195.2  2020.6
   230.5 2020.71   292.3 2016.57   407.2 2017.84   411.6 2017.52   424.9 2014.01
   438.1 2015.15   446.8 2014.32   455.8  2014.8   473.82012.489   477.9 2011.06
   485.9  2010.9   508.8 2011.37   513.8 2012.46     519 2014.23   526.5 2013.06
   531.4 2013.22   540.1 2016.15   544.1 2018.88     553 2028.15   564.1 2036.59
   570.1 2040.51   578.5  2043.5   645.3 2058.59   663.4 2060.38   692.6 2060.81
#Mann= 4 ,-1,0
       0     .05       0     410      .1       0   473.8    .045       0
   513.8      .1       0
Bank Sta=473.8,513.8
XS Rating Curve= 0 ,0
Exp/Cntr(USF)=0,0
Exp/Cntr=0.3,0.1

Type RM Length L Ch R = 1 ,3425    ,490.1,504.8,518.4
XS GIS Cut Line= 3
2272094.38380829 641902.78519362 2272509.6163074642101.260628802
2272604.53830405642258.898944679
#Sta/Elev= 30
       0 2015.55    51.1 2015.79    90.1 2013.95   129.1 2015.09   188.2 2013.83
     268 2015.04   272.4 2014.23   276.9 2012.46   283.8 2011.34   330.2 2013.37
   356.7 2011.01   360.1 2009.96   366.1 2008.81   396.6 2008.95     401 2009.99
   405.4 2012.61   414.3 2014.04   427.6 2014.38   447.1 2013.54   454.2 2013.61
   458.6 2014.24   476.6 2022.98   483.5 2027.61   496.2 2037.62   502.2 2039.43
   526.1 2041.71   546.5 2044.81   576.9 2047.52   604.9 2051.01   644.2 2054.89
#Mann= 5 ,-1,0
       0     .05       0     220      .1       0   360.1    .045       0
     401      .1       0  620.23     .05       0
#XS Ineff= 2 , 0
          280.51 2020.96
Permanent Ineff=
       F       F
Bank Sta=360.1,401
XS Rating Curve= 0 ,0
Exp/Cntr(USF)=0,0
Exp/Cntr=0.3,0.1

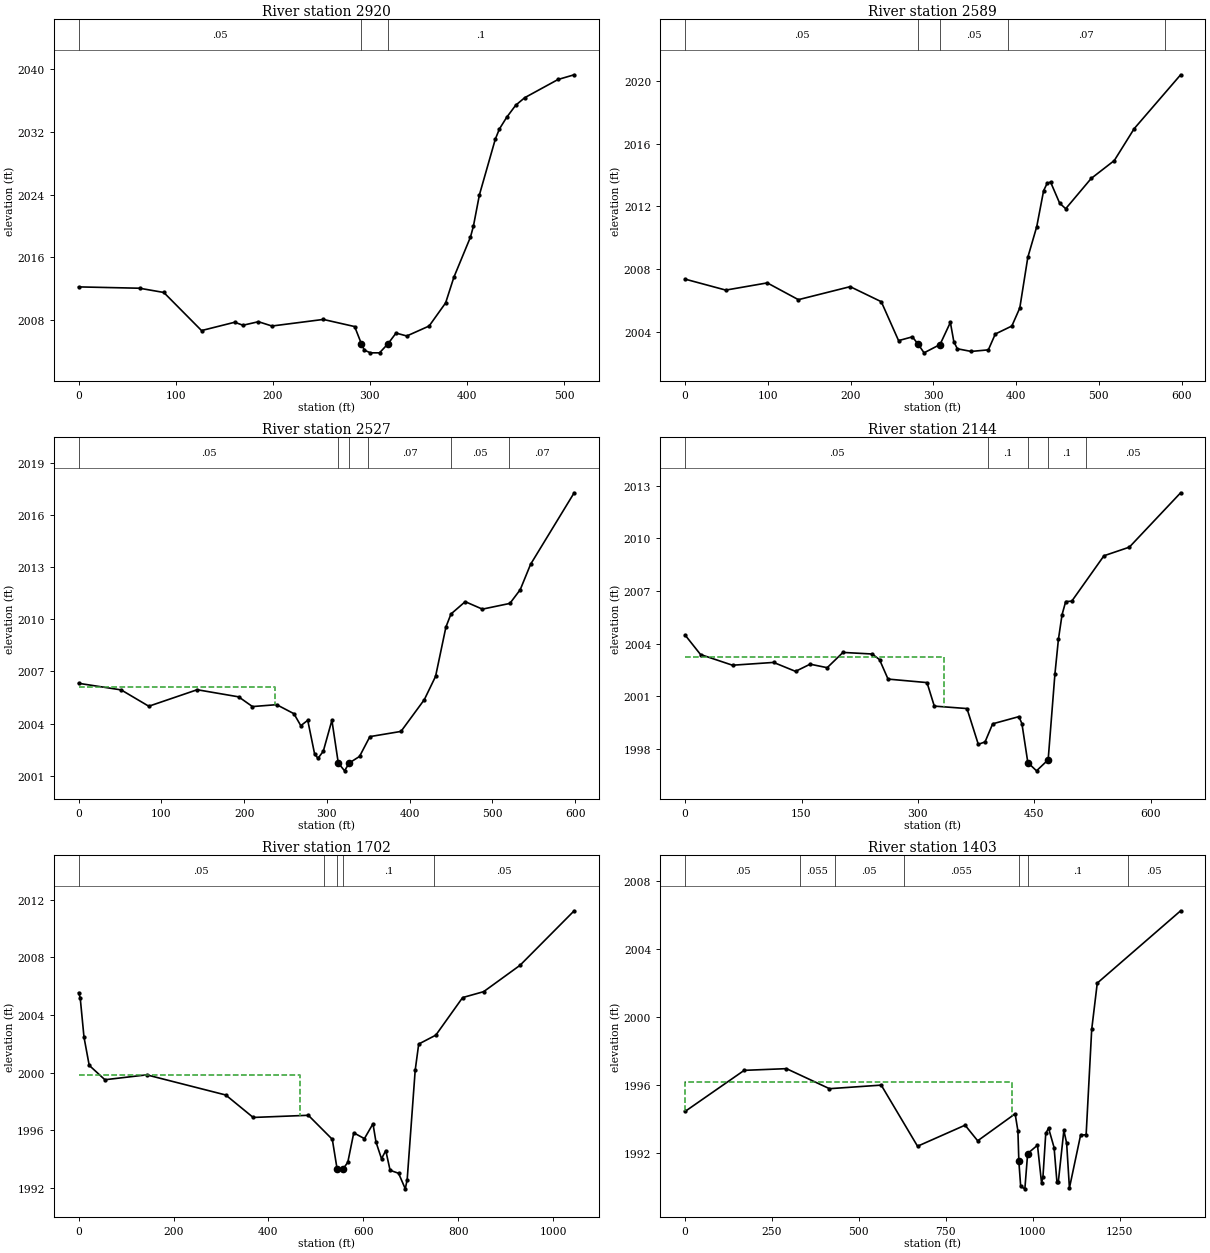
Type RM Length L Ch R = 1 ,2920    ,322.1,330.8,324.9
XS GIS Cut Line= 2
2271937.38482623642058.2778728212272113.16630152642537.491656648
#Sta/Elev= 30
       0 2012.25    62.7 2012.08    87.7 2011.54   126.6 2006.68   160.7 2007.74
   169.3 2007.36   185.2 2007.81   199.1 2007.26     252  2008.1   284.3 2007.19
   291.2 2005.01   294.3 2004.18   300.6 2003.84   309.9 2003.84   318.72005.001
   326.9 2006.36     338 2005.99     361 2007.26     378 2010.21   386.5 2013.48
   403.6 2018.61   406.6 2019.98   412.8 2023.99   429.2  2031.1   433.4 2032.39
   440.8 2033.86   450.2 2035.42   459.5 2036.38   493.8  2038.7   510.4  2039.3
#Mann= 3 ,-1,0
       0     .05       0   291.2    .045       0   318.7      .1       0
Bank Sta=291.2,318.7
XS Rating Curve= 0 ,0
Exp/Cntr(USF)=0,0
Exp/Cntr=0.3,0.1

Type RM Length L Ch R = 1 ,2589    ,86.5,61.7,77.2
XS GIS Cut Line= 3
2271659.83836048642162.0194445832271791.67446695642602.728714776
2271925.39394637642565.061255785
#Sta/Elev= 30
       0 2007.36    49.2 2006.66    99.3 2007.12   136.9 2006.05   199.5 2006.88
   237.1 2005.92     258 2003.44   274.7 2003.68   281.92003.192   288.8 2002.66
   308.1 2003.19   320.6  2004.6   324.8 2003.37     329 2002.92   345.7 2002.75
   366.5 2002.85   374.9 2003.86   394.9 2004.37   404.5 2005.52   414.2 2008.75
     425 2010.71   433.3    2013   437.5 2013.46   441.7 2013.55   452.7  2012.2
     460 2011.85   490.8 2013.78   518.7 2014.92   542.7 2016.95   598.9 2020.39
#Mann= 5 ,-1,0
       0     .05       0   281.9    .045       0   308.1     .05       0
     390     .07       0  580.01     .06       0
Bank Sta=281.9,308.1
XS Rating Curve= 0 ,0
Exp/Cntr(USF)=0,0
Exp/Cntr=0.3,0.1

Type RM Length L Ch R = 1 ,2527    ,371.1,383.1,377.4
XS GIS Cut Line= 3
2271609.40069121642203.9222326632271741.23679768642644.631502856
2271874.95627709642606.964043865
#Sta/Elev= 30
       0 2006.32    51.4 2005.94    84.8    2005   143.3 2005.95   193.4 2005.54
   210.1 2004.98   239.3 2005.09   260.2 2004.57   268.5 2003.88   276.9 2004.19
   285.2 2002.25   289.3    2002   295.7 2002.41   306.1 2004.19   313.82001.733
   321.4 2001.28     327 2001.73   339.5 2002.11     352 2003.25   389.6 2003.55
   417.8 2005.38   431.4 2006.72   443.9 2009.56     450 2010.31   467.2 2011.02
     488 2010.59   521.2 2010.92   533.7 2011.71   546.2 2013.17   598.9 2017.29
#Mann= 6 ,-1,0
       0     .05       0   313.8    .045       0     327     .05       0
     350     .07       0     450     .05       0  520.01     .07       0
#XS Ineff= 2 , 0
          237.83  2006.1
Permanent Ineff=
       F       F
Bank Sta=313.8,327
XS Rating Curve= 0 ,0
Exp/Cntr(USF)=0,0
Exp/Cntr=0.3,0.1

Type RM Length L Ch R = 1 ,2144    ,438.7,442.7,442.7
XS GIS Cut Line= 3
2271233.08922993642400.2180695542271494.46879865642822.292709908
2271631.95502396642858.076795949
#Sta/Elev= 30
       0 2004.49    19.9 2003.38    61.1 2002.77     114 2002.93   142.3 2002.42
   161.1 2002.83   183.1 2002.63   203.4  2003.5   241.1 2003.41   250.5 2003.09
   261.5 2001.98   311.7 2001.78   321.1 2000.44   363.2  2000.3   377.8 1998.26
   386.5  1998.4   396.3 1999.43   430.1 1999.84     434 1999.44   441.61997.225
   452.8 1996.75   467.8 1997.38   476.5 2002.26     481 2004.24   485.7 2005.65
   490.4  2006.4   498.2 2006.42   539.7 2009.01   572.4  2009.5   638.5  2012.6
#Mann= 5 ,-1,0
       0     .05       0     390      .1       0   441.6    .045       0
   467.8      .1       0  516.45     .05       0
#XS Ineff= 2 , 0
          334.06 2003.25
Permanent Ineff=
       F       F
Bank Sta=441.6,467.8
XS Rating Curve= 0 ,0
Exp/Cntr(USF)=0,0
Exp/Cntr=0.3,0.1

Type RM Length L Ch R = 1 ,1702    ,306.1,298.4,285.3
XS GIS Cut Line= 4
2270984.12438997642437.8684114112270971.36635546  642724.9241879
2271149.97883861643072.5806283142271513.58282216643117.233749101
#Sta/Elev= 30
       0 2005.55     3.3  2005.2    11.3 2002.46    22.3  2000.5    55.4  1999.5
   143.5 1999.84   310.1 1998.44   367.9 1996.88   484.2 1997.03   534.7 1995.36
   544.81993.301   557.4  1993.3   567.4 1993.77   579.9 1995.81   602.4 1995.41
   620.4 1996.44   626.8 1995.17   638.4 1994.01   647.4 1994.58   656.5 1993.21
   674.4    1993   688.5 1991.92   692.5 1992.55   709.4 2000.16   716.8 2001.98
   752.9  2002.6   809.4 2005.21   853.7 2005.62   930.3 2007.45  1044.5 2011.24
#Mann= 5 ,-1,0
       0     .05       0  517.34      .1       0   544.8    .045       0
   557.4      .1       0  748.19     .05       0
#XS Ineff= 2 , 0
          465.57  1999.8
Permanent Ineff=
       F       F
Bank Sta=544.8,557.4
XS Rating Curve= 0 ,0
Exp/Cntr(USF)=0,0
Exp/Cntr=0.3,0.1

Type RM Length L Ch R = 1 ,1403    ,396.1,396.1,396.1
XS GIS Cut Line= 3
2270702.30045375642308.0602622732270792.18867343643156.774568228
2271363.67591666643187.402938909
#Sta/Elev= 30
       0 1994.42     170 1996.84   291.6 1996.94   415.4 1995.76   564.3 1995.97
   668.8 1992.37   805.6 1993.61   841.8 1992.69   949.6 1994.28   957.6 1993.27
 960.3041991.477   965.6    1990   977.6 1989.86 985.604 1991.94  1013.9 1992.43
  1025.7 1990.19  1029.7 1990.58  1037.7 1993.12  1045.7 1993.44  1061.7 1992.29
  1069.8 1990.28  1073.8 1990.26  1089.8  1993.3  1097.8 1992.55  1105.8 1989.91
  1137.9 1993.02  1153.9 1993.05  1169.9 1999.25  1185.9 2001.98  1425.8 2006.24
#Mann= 7 ,-1,0
       0     .05       0     330    .055       0     430     .05       0
     630    .055       0 960.304    .045       0 985.604      .1       0
 1273.46     .05       0
#XS Ineff= 2 , 0
          941.35 1996.16
Permanent Ineff=
       F       F
Bank Sta=960.304,985.604
XS Rating Curve= 0 ,0
Exp/Cntr(USF)=0,0
Exp/Cntr=0.3,0.1

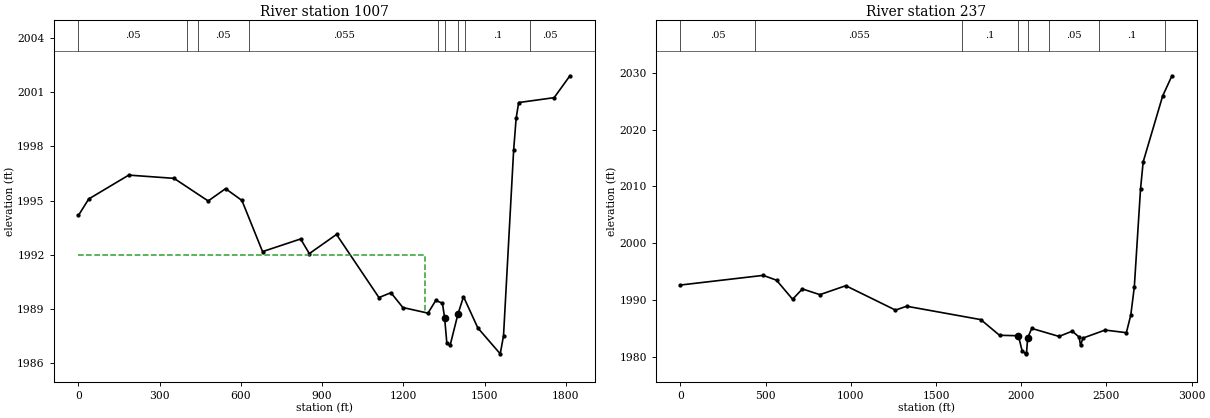
Type RM Length L Ch R = 1 ,1007    ,770.4,770.4,770.4
XS GIS Cut Line= 4
 2270681.5289125642300.1109943132270790.65100292 643494.39165056
2271130.14195089643567.1397108392271372.63548515643451.955282064
#Sta/Elev= 30
       0 1994.18      38 1995.09   185.8 1996.41   353.1 1996.23   479.1 1994.98
   543.3 1995.66   603.6 1995.01   679.9 1992.18   820.5 1992.88   852.6 1992.07
     953 1993.13  1109.7 1989.64  1153.9 1989.91    1198 1989.09  1290.8 1988.78
  1319.4 1989.48    1344 1989.33  1352.2 1988.52  1360.4 1987.12  1372.6 1987.01
  1401.3 1988.72  1421.9 1989.69  1474.9 1987.96  1557.6 1986.53  1569.7 1987.53
    1607 1997.78  1616.3 1999.55  1625.6 2000.42  1756.6 2000.691814.913  2001.9
#Mann= 9 ,-1,0
       0     .05       0     400    .055       0     440     .05       0
     630    .055       0 1329.26     .05       0  1352.2    .045       0
  1401.3     .05       0 1429.26      .1       0 1666.45     .05       0
#XS Ineff= 2 , 0
         1278.69 1991.97
Permanent Ineff=
       F       F
Bank Sta=1352.2,1401.3
XS Rating Curve= 0 ,0
Exp/Cntr(USF)=0,0
Exp/Cntr=0.3,0.1

Type RM Length L Ch R = 1 ,237     ,,,
XS GIS Cut Line= 5
2270473.13474394642304.1162839332270872.76139539 644023.57121554
2271033.55630393644071.1048635322271137.84153477644028.789838086
2271673.47773854643383.212511405
#Sta/Elev= 30
       0 1992.63  485.67 1994.33   563.7 1993.48  658.15 1990.12  715.64 1991.94
  818.31 1990.93  970.25 1992.51 1261.82 1988.21 1327.53 1988.89  1762.8 1986.53
 1872.35 1983.77 1983.27 1983.69 2004.85 1981.05 2026.44  1980.5 2030.75 1980.64
 2037.78 1983.34 2061.68 1984.98 2221.71 1983.57 2299.67  1984.5 2339.47 1983.45
 2347.99 1982.01 2362.05 1983.28 2491.98 1984.69 2616.72 1984.23 2642.71 1987.32
  2663.5 1992.29 2699.89 2009.55 2715.48 2014.34 2829.82 2025.95 2884.35 2029.51
#Mann= 8 ,-1,0
       0     .05       0     440    .055       0    1650      .1       0
 1983.27    .045       0 2037.78      .1       0  2165.5     .05       0
  2455.5      .1       0  2845.5     .05       0
Bank Sta=1983.27,2037.78
XS Rating Curve= 0 ,0
Exp/Cntr(USF)=0,0
Exp/Cntr=0.3,0.1
LCMann Table=0

Chan Stop Cuts=-1
Use User Specified Reach Order=0
Composite Channel Slope=5